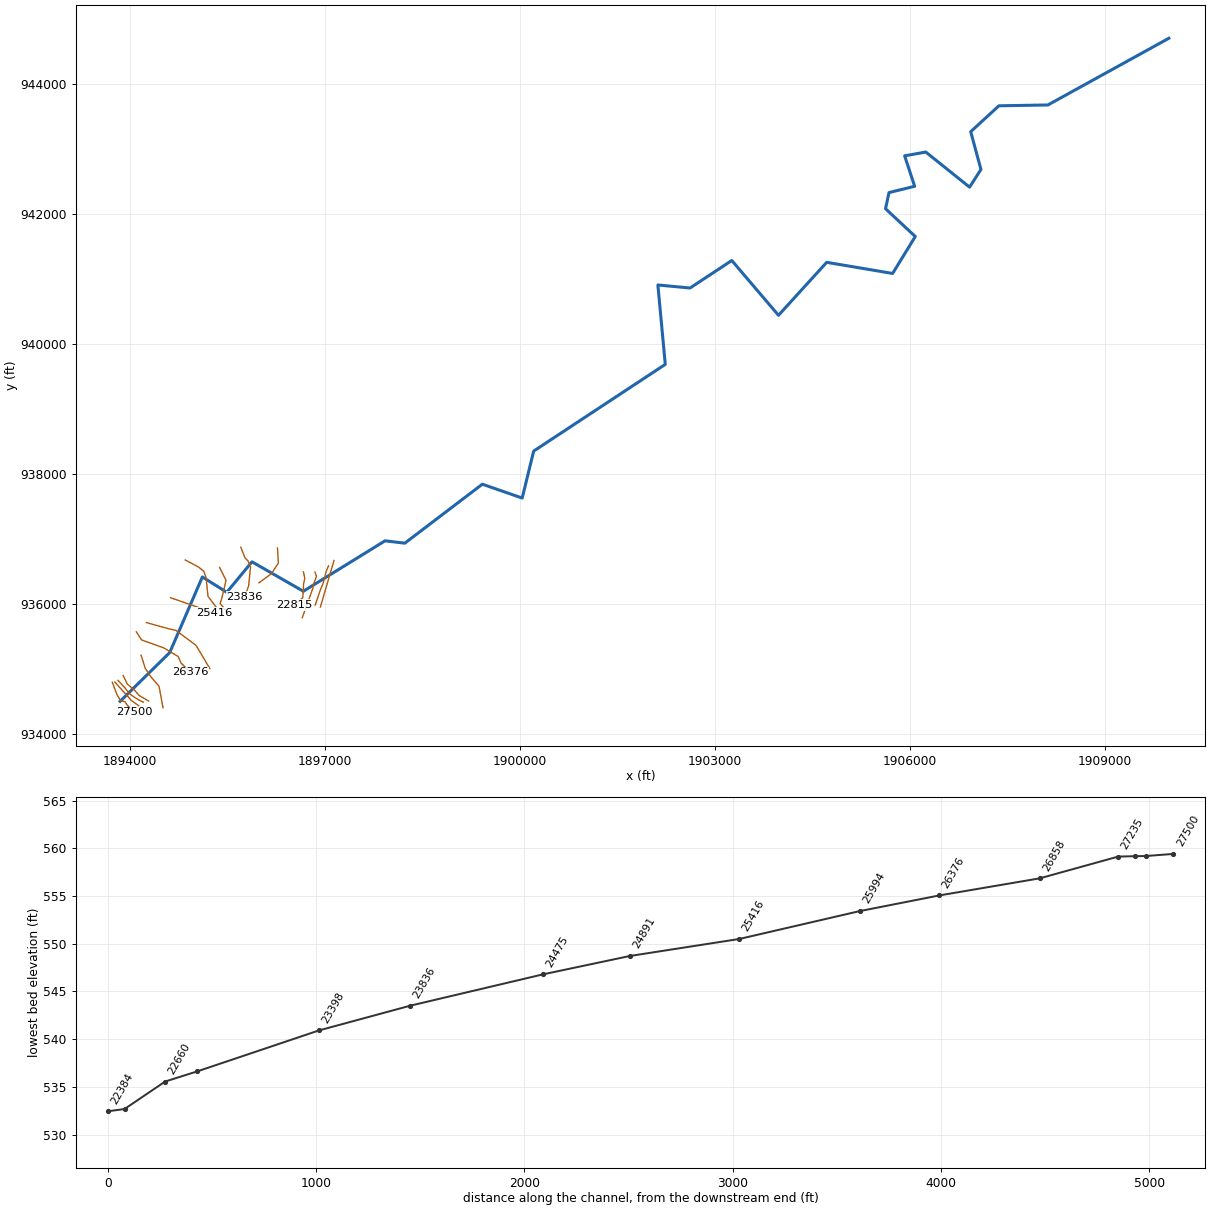
--- Burkes.prj (project) ---

Proj Title=Burkes Creek
Current Plan=p04
Default Exp/Contr=0.3,0.1
English Units
Geom File=g03
Flow File=f02
Flow File=f01
Plan File=p04
Y Axis Title=Elevation
X Axis Title(PF)=Main Channel Distance
X Axis Title(XS)=Station
BEGIN DESCRIPTION:
END DESCRIPTION:
DSS Export Rating Curves= 0
DSS Export Rating Curve Sorted= 0
DSS Export Volume Flow Curves= 0
DXF OffsetX= 0
DXF OffsetY= 0
DXF ScaleX= 1
DXF ScaleY= 10

--- Burkes.p04 (plan) ---

Plan Title=Floodway
Program Version=3.11
Short Identifier=Fldwy
Geom File=g03
Flow File=f02
Subcritical Flow
K Sum by GR= 0
Std Step Tol= 0.01
Critical Tol= 0.01
Num of Std Step Trials= 20
Max Error Tol= 0.3
Flow Tol Ratio= 0.001
Split Flow NTrial= 30
Split Flow Tol= 0.02
Split Flow Ratio= 0.02
Log Output Level= 0
Friction Slope Method= 1
Unsteady Friction Slope Method= 2
Unsteady Bridges Friction Slope Method= 1
Parabolic Critical Depth
Global Vel Dist= 0 , 0 , 0
Global Log Level= 0
CheckData=True
Encroach Param=-1 ,0,0, 2
Encroach River=BUR
Encroach Reach=BUR
Encroach Node=27500
       1  357.47  449.55
Encroach Node=27370
       1  205.61  291.08
Encroach Node=27344
       4      .7
Encroach Node=27317
       1  181.46   258.3
Encroach Node=27235
       1  192.41  248.88
Encroach Node=26858
       1  266.07  322.82
Encroach Node=26376
       1  605.71  659.14
Encroach Node=25994
       1  373.54  455.21
Encroach Node=25416
       1  286.99  345.04
Encroach Node=24891
       1  380.89  427.17
Encroach Node=24475
       1  400.79  452.93
Encroach Node=23836
       1  248.64  292.54
Encroach Node=23398
       1  288.76  332.91
Encroach Node=22815
       1  293.33  337.41
Encroach Node=22660
       1     187     247
Encroach Node=22561
       4      .7
Encroach Node=22465
       1     191     223
Encroach Node=22384
       1     226     285
Encroach Node=21899
       1     312     356
Encroach Node=20774
       1  450.09  509.85
Encroach Node=20246
       1  504.25  563.23
Encroach Node=19297
       1  307.16  357.88
Encroach Node=18634
       1  832.84  876.81
Encroach Node=17675
       1   441.3   493.9
Encroach Node=17165
       1  401.87  454.19
Encroach Node=16543
       1  314.13  356.15
Encroach Node=15744
       1  491.91  576.31
Encroach Node=15033
       1   363.9  414.74
Encroach Node=14344
       1  346.23  451.79
Encroach Node=13719
       1  616.84  674.88
Encroach Node=13007
       1  443.27  494.39
Encroach Node=12187
       1  347.71  410.93
Encroach Node=11361
       1   333.7   376.6
Encroach Node=11011
       1  328.93  516.22
Encroach Node=10214
       1  407.97   466.7
Encroach Node=9137
       1  348.65  430.66
Encroach Node=8401
       1  455.06  529.32
Encroach Node=7662
       1  528.22  577.94
Encroach Node=6856
       1   458.6  536.72
Encroach Node=5694
       1  351.65  412.62
Encroach Node=5111
       1  625.52  681.89
Encroach Node=4698
       1     240     284
Encroach Node=4092
       1     598     647
Encroach Node=3730
       1  283.09  333.34
Encroach Node=3416
       4      .7
Encroach Node=3045
       1  337.63  399.24
Encroach Node=2309
       1  420.49  484.24
Encroach Node=1480
       1  444.91     503
Encroach Node=932
       1     527  606.57
Encroach Node=535
       1     610     770
Computation Interval=1HOUR
Output Interval=1HOUR
Run HTab= 0
Run UNet= 0
Run PostProcess= 0
UNET Theta= 1
UNET Theta Warmup= 1
UNET ZTol= 0.02
UNET ZSATol= 0.05
UNET MxIter= 20
UNET MaxInSteps= 0
UNET DtIC= 0
UNET DtMin= 0
UNET MaxCRTS= 20
UNET WFStab= 2
UNET SFStab= 1
UNET WFX= 1
UNET SFX= 1
UNET DSS MLevel= 4
UNET DZMax Abort= 100
UNET Convert EG Bridges=-1
UNET Use Existing IB Tables=-1
UNET Froude Reduction=False
UNET Froude Limit= 1
UNET Froude Power= 10
Instantaneous Interval=1HOUR
Write IC File= 0
Echo Input=False
Echo Output=False
Write Detailed= 0
Detailed Automatic Start=False, 10

--- Burkes.f02 (steady flow) ---

Flow Title=Floodway Flowrates
Program Version=3.11
Number of Profiles= 2
Profile Names=100-year,Floodway
River Rch & RM=SCLT4,SCLT4           ,7544
  892.78  892.78
River Rch & RM=SCLT4,SCLT4           ,5978
 1027.05 1027.05
River Rch & RM=SCLT4,SCLT4           ,2566
 1140.95 1140.95
River Rch & RM=SCLT3,SCLT3           ,4618
  903.01  903.01
River Rch & RM=SCLT3,SCLT3           ,3669
  978.55  978.55
River Rch & RM=SCLT3,SCLT3           ,2646
 1098.31 1098.31
River Rch & RM=SCLT2A1,SCLT2A1         ,2036
  580.69  580.69
River Rch & RM=SCLT2A1,SCLT2A1         ,1426
  626.24  626.24
River Rch & RM=SCLT2A,SCLT2A          ,9271
   671.1   671.1
River Rch & RM=SCLT2A,SCLT2A          ,8447
  754.88  754.88
River Rch & RM=SCLT2A,SCLT2A          ,5640
 1101.52 1101.52
River Rch & RM=SCLT2A,SCLT2A          ,3764
 1271.42 1271.42
River Rch & RM=SCLT2A,SCLT2A          ,2070
 1550.76 1550.76
River Rch & RM=SCLT2,SCLT2           ,15367
  750.36  750.36
River Rch & RM=SCLT2,SCLT2           ,13298
  890.04  890.04
River Rch & RM=SCLT2,SCLT2           ,9472
   984.1   984.1
River Rch & RM=SCLT2,SCLT2           ,6171
 2049.16 2049.16
River Rch & RM=SCLT2,SCLT2           ,1541
 2199.92 2199.92
River Rch & RM=SCLT1,SCLT1           ,874
 1171.03 1171.03
River Rch & RM=SCL,SCL             ,68195
  780.67  780.67
River Rch & RM=SCL,SCL             ,67410
  835.83  835.83
River Rch & RM=SCL,SCL             ,65956
 1070.71 1070.71
River Rch & RM=SCL,SCL             ,64299
 1287.13 1287.13
River Rch & RM=SCL,SCL             ,62283
 1556.72 1556.72
River Rch & RM=SCL,SCL             ,61272
 1682.49 1682.49
River Rch & RM=SCL,SCL             ,59972
 1813.28 1813.28
River Rch & RM=SCL,SCL             ,55662
 1949.14 1949.14
River Rch & RM=SCL,SCL             ,53257
 2071.73 2071.73
River Rch & RM=SCL,SCL             ,49493
 2935.78 2935.78
River Rch & RM=SCL,SCL             ,48712
 2964.67 2964.67
River Rch & RM=SCL,SCL             ,48602
 2964.67 2964.67
River Rch & RM=SCL,SCL             ,46045
  2994.8  2994.8
River Rch & RM=SCL,SCL             ,43512
 3112.39 3112.39
River Rch & RM=SCL,SCL             ,39744
 3114.72 3114.72
River Rch & RM=SCL,SCL             ,36134
 3127.73 3127.73
River Rch & RM=SCL,SCL             ,33745
  3152.6  3152.6
River Rch & RM=SCL,SCL             ,31983
 4273.14 4273.14
River Rch & RM=SCL,SCL             ,28770
 6082.38 6082.38
River Rch & RM=SCL,SCL             ,27109
  6840.1  6840.1
River Rch & RM=SCL,SCL             ,22124
    7099    7099
River Rch & RM=SCL,SCL             ,20504
 7268.11 7268.11
River Rch & RM=SCL,SCL             ,13626
 7495.21 7495.21
River Rch & RM=SCL,SCL             ,10568
 7589.89 7589.89
River Rch & RM=SCL,SCL             ,9280
 7675.75 7675.75
River Rch & RM=SCL,SCL             ,7290
 7893.16 7893.16
River Rch & RM=SCL,SCL             ,4386
 7913.45 7913.45
River Rch & RM=SCL,SCL             ,2509
 7965.84 7965.84
River Rch & RM=PEN,PEN             ,33841
  913.91  913.91
River Rch & RM=PEN,PEN             ,31578
   968.6   968.6
River Rch & RM=PEN,PEN             ,30461
  1095.7  1095.7
River Rch & RM=PEN,PEN             ,28488
 1134.96 1134.96
River Rch & RM=PEN,PEN             ,27444
 1361.09 1361.09
River Rch & RM=PEN,PEN             ,24704
 1539.41 1539.41
River Rch & RM=PEN,PEN             ,21666
  1627.7  1627.7
River Rch & RM=PEN,PEN             ,20471
 1648.75 1648.75
River Rch & RM=PEN,PEN             ,19297
 1821.94 1821.94
River Rch & RM=PEN,PEN             ,14745
 1911.95 1911.95
River Rch & RM=PEN,PEN             ,13265
  1999.4  1999.4
River Rch & RM=PEN,PEN             ,11323
 2084.27 2084.27
River Rch & RM=PEN,PEN             ,9298
 2151.61 2151.61
River Rch & RM=PEN,PEN             ,5604
 3480.39 3480.39
River Rch & RM=PEN,PEN             ,4359
 3542.08 3542.08
River Rch & RM=PEN,PEN             ,2491
 3586.54 3586.54
River Rch & RM=BYR,BYR             ,27961
  916.75  916.75
River Rch & RM=BYR,BYR             ,27398
 1037.48 1037.48
River Rch & RM=BYR,BYR             ,25766
 1157.05 1157.05
River Rch & RM=BYR,BYR             ,24178
 1273.55 1273.55
River Rch & RM=BYR,BYR             ,21031
 1324.88 1324.88
River Rch & RM=BYR,BYR             ,20458
 1677.38 1677.38
River Rch & RM=BYR,BYR             ,18389
 1766.81 1766.81
River Rch & RM=BYR,BYR             ,16473
 1858.27 1858.27
River Rch & RM=BYR,BYR             ,14096
 1929.24 1929.24
River Rch & RM=BYR,BYR             ,11163
 2012.58 2012.58
River Rch & RM=BYR,BYR             ,9853
  2081.1  2081.1
River Rch & RM=BYR,BYR             ,7757
 2159.55 2159.55
River Rch & RM=BYR,BYR             ,6282
  2236.1  2236.1
River Rch & RM=BYR,BYR             ,3110
 2309.79 2309.79
River Rch & RM=BUR,BUR             ,27500
 1612.84 1612.84
River Rch & RM=BUR,BUR             ,23398
 1695.56 1695.56
River Rch & RM=BUR,BUR             ,20774
 1728.18 1728.18
River Rch & RM=BUR,BUR             ,20246
 1820.98 1820.98
River Rch & RM=BUR,BUR             ,19297
 1905.71 1905.71
River Rch & RM=BUR,BUR             ,16543
 1985.15 1985.15
River Rch & RM=BUR,BUR             ,14344
 2056.55 2056.55
River Rch & RM=BUR,BUR             ,11011
 2134.14 2134.14
River Rch & RM=BUR,BUR             ,7662
 2208.06 2208.06
River Rch & RM=BUR,BUR             ,3045
 2284.56 2284.56
River Rch & RM=BGL,BGL             ,2467
  1004.3  1004.3
River Rch & RM=BGL,BGL             ,1003
 1021.21 1021.21
Boundary for River Rch & Prof#=BYR,BYR             , 1
Up Type= 0
Dn Type= 3
Dn Slope=0.0049
Boundary for River Rch & Prof#=BYR,BYR             , 2
Up Type= 0
Dn Type= 3
Dn Slope=0.0049
Boundary for River Rch & Prof#=SCL,SCL             , 1
Up Type= 0
Dn Type= 3
Dn Slope=0.00067
Boundary for River Rch & Prof#=SCL,SCL             , 2
Up Type= 0
Dn Type= 3
Dn Slope=0.00067
Boundary for River Rch & Prof#=BUR,BUR             , 1
Up Type= 0
Dn Type= 3
Dn Slope=0.0021
Boundary for River Rch & Prof#=BUR,BUR             , 2
Up Type= 0
Dn Type= 3
Dn Slope=0.0021
Boundary for River Rch & Prof#=PEN,PEN             , 1
Up Type= 0
Dn Type= 3
Dn Slope=0.023
Boundary for River Rch & Prof#=PEN,PEN             , 2
Up Type= 0
Dn Type= 3
Dn Slope=0.023
Boundary for River Rch & Prof#=SCLT4,SCLT4           , 1
Up Type= 0
Dn Type= 3
Dn Slope=0.0082
Boundary for River Rch & Prof#=SCLT4,SCLT4           , 2
Up Type= 0
Dn Type= 3
Dn Slope=0.0082
Boundary for River Rch & Prof#=SCLT3,SCLT3           , 1
Up Type= 0
Dn Type= 3
Dn Slope=0.016
Boundary for River Rch & Prof#=SCLT3,SCLT3           , 2
Up Type= 0
Dn Type= 3
Dn Slope=0.016
Boundary for River Rch & Prof#=SCLT2,SCLT2           , 1
Up Type= 0
Dn Type= 3
Dn Slope=0.003
Boundary for River Rch & Prof#=SCLT2,SCLT2           , 2
Up Type= 0
Dn Type= 3
Dn Slope=0.003
Boundary for River Rch & Prof#=SCLT2A,SCLT2A          , 1
Up Type= 0
Dn Type= 3
Dn Slope=0.0038
Boundary for River Rch & Prof#=SCLT2A,SCLT2A          , 2
Up Type= 0
Dn Type= 3
Dn Slope=0.0038
Boundary for River Rch & Prof#=SCLT2A1,SCLT2A1         , 1
Up Type= 0
Dn Type= 3
Dn Slope=0.016
Boundary for River Rch & Prof#=SCLT2A1,SCLT2A1         , 2
Up Type= 0
Dn Type= 3
Dn Slope=0.016
Boundary for River Rch & Prof#=BGL,BGL             , 1
Up Type= 0
Dn Type= 3
Dn Slope=0.0076
Boundary for River Rch & Prof#=BGL,BGL             , 2
Up Type= 0
Dn Type= 3
Dn Slope=0.0076
Boundary for River Rch & Prof#=SCLT1,SCLT1           , 1
Up Type= 0
Dn Type= 3
Dn Slope=0.0025
Boundary for River Rch & Prof#=SCLT1,SCLT1           , 2
Up Type= 0
Dn Type= 3
Dn Slope=0.0025
DSS Import GetInterval= 0
DSS Import GetPeak= 0
DSS Import FillOption= 0

--- Burkes.f01 (steady flow) ---

Flow Title=100-year discharge
Program Version=3.11
Number of Profiles= 1
Profile Names=100-year
River Rch & RM=SCLT4,SCLT4           ,7544
  892.78
River Rch & RM=SCLT4,SCLT4           ,5978
 1027.05
River Rch & RM=SCLT4,SCLT4           ,2566
 1140.95
River Rch & RM=SCLT3,SCLT3           ,4618
  903.01
River Rch & RM=SCLT3,SCLT3           ,3669
  978.55
River Rch & RM=SCLT3,SCLT3           ,2646
 1098.31
River Rch & RM=SCLT2A1,SCLT2A1         ,2036
  580.69
River Rch & RM=SCLT2A1,SCLT2A1         ,1426
  626.24
River Rch & RM=SCLT2A,SCLT2A          ,9271
   671.1
River Rch & RM=SCLT2A,SCLT2A          ,8447
  754.88
River Rch & RM=SCLT2A,SCLT2A          ,5640
 1101.52
River Rch & RM=SCLT2A,SCLT2A          ,3764
 1271.42
River Rch & RM=SCLT2A,SCLT2A          ,2070
 1550.76
River Rch & RM=SCLT2,SCLT2           ,15367
  750.36
River Rch & RM=SCLT2,SCLT2           ,13298
  890.04
River Rch & RM=SCLT2,SCLT2           ,9472
   984.1
River Rch & RM=SCLT2,SCLT2           ,6171
 2049.16
River Rch & RM=SCLT2,SCLT2           ,1541
 2199.92
River Rch & RM=SCLT1,SCLT1           ,874
 1171.03
River Rch & RM=SCL,SCL             ,68195
  780.67
River Rch & RM=SCL,SCL             ,67410
  835.83
River Rch & RM=SCL,SCL             ,65956
 1070.71
River Rch & RM=SCL,SCL             ,64299
 1287.13
River Rch & RM=SCL,SCL             ,62283
 1556.72
River Rch & RM=SCL,SCL             ,61272
 1682.49
River Rch & RM=SCL,SCL             ,59972
 1813.28
River Rch & RM=SCL,SCL             ,55662
 1949.14
River Rch & RM=SCL,SCL             ,53257
 2071.73
River Rch & RM=SCL,SCL             ,49493
 2935.78
River Rch & RM=SCL,SCL             ,48712
 2964.67
River Rch & RM=SCL,SCL             ,48602
 2964.67
River Rch & RM=SCL,SCL             ,46045
  2994.8
River Rch & RM=SCL,SCL             ,43512
 3112.39
River Rch & RM=SCL,SCL             ,39744
 3114.72
River Rch & RM=SCL,SCL             ,36134
 3127.73
River Rch & RM=SCL,SCL             ,33745
  3152.6
River Rch & RM=SCL,SCL             ,31983
 4273.14
River Rch & RM=SCL,SCL             ,28770
 6082.38
River Rch & RM=SCL,SCL             ,27109
  6840.1
River Rch & RM=SCL,SCL             ,22124
    7099
River Rch & RM=SCL,SCL             ,20504
 7268.11
River Rch & RM=SCL,SCL             ,13626
 7495.21
River Rch & RM=SCL,SCL             ,10568
 7589.89
River Rch & RM=SCL,SCL             ,9280
 7675.75
River Rch & RM=SCL,SCL             ,7290
 7893.16
River Rch & RM=SCL,SCL             ,4386
 7913.45
River Rch & RM=SCL,SCL             ,2509
 7965.84
River Rch & RM=PEN,PEN             ,33841
  913.91
River Rch & RM=PEN,PEN             ,31578
   968.6
River Rch & RM=PEN,PEN             ,30461
  1095.7
River Rch & RM=PEN,PEN             ,28488
 1134.96
River Rch & RM=PEN,PEN             ,27444
 1361.09
River Rch & RM=PEN,PEN             ,24704
 1539.41
River Rch & RM=PEN,PEN             ,21666
  1627.7
River Rch & RM=PEN,PEN             ,20471
 1648.75
River Rch & RM=PEN,PEN             ,19297
 1821.94
River Rch & RM=PEN,PEN             ,14745
 1911.95
River Rch & RM=PEN,PEN             ,13265
  1999.4
River Rch & RM=PEN,PEN             ,11323
 2084.27
River Rch & RM=PEN,PEN             ,9298
 2151.61
River Rch & RM=PEN,PEN             ,5604
 3480.39
River Rch & RM=PEN,PEN             ,4359
 3542.08
River Rch & RM=PEN,PEN             ,2491
 3586.54
River Rch & RM=BYR,BYR             ,27961
  916.75
River Rch & RM=BYR,BYR             ,27398
 1037.48
River Rch & RM=BYR,BYR             ,25766
 1157.05
River Rch & RM=BYR,BYR             ,24178
 1273.55
River Rch & RM=BYR,BYR             ,21031
 1324.88
River Rch & RM=BYR,BYR             ,20458
 1677.38
River Rch & RM=BYR,BYR             ,18389
 1766.81
River Rch & RM=BYR,BYR             ,16473
 1858.27
River Rch & RM=BYR,BYR             ,14096
 1929.24
River Rch & RM=BYR,BYR             ,11163
 2012.58
River Rch & RM=BYR,BYR             ,9853
  2081.1
River Rch & RM=BYR,BYR             ,7757
 2159.55
River Rch & RM=BYR,BYR             ,6282
  2236.1
River Rch & RM=BYR,BYR             ,3110
 2309.79
River Rch & RM=BUR,BUR             ,27500
 1612.84
River Rch & RM=BUR,BUR             ,23398
 1695.56
River Rch & RM=BUR,BUR             ,20774
 1728.18
River Rch & RM=BUR,BUR             ,20246
 1820.98
River Rch & RM=BUR,BUR             ,19297
 1905.71
River Rch & RM=BUR,BUR             ,16543
 1985.15
River Rch & RM=BUR,BUR             ,14344
 2056.55
River Rch & RM=BUR,BUR             ,11011
 2134.14
River Rch & RM=BUR,BUR             ,7662
 2208.06
River Rch & RM=BUR,BUR             ,3045
 2284.56
River Rch & RM=BGL,BGL             ,2467
  1004.3
River Rch & RM=BGL,BGL             ,1003
 1021.21
Boundary for River Rch & Prof#=BYR,BYR             , 1
Up Type= 0
Dn Type= 3
Dn Slope=0.0049
Boundary for River Rch & Prof#=SCL,SCL             , 1
Up Type= 0
Dn Type= 3
Dn Slope=0.00067
Boundary for River Rch & Prof#=BUR,BUR             , 1
Up Type= 0
Dn Type= 3
Dn Slope=0.0021
Boundary for River Rch & Prof#=PEN,PEN             , 1
Up Type= 0
Dn Type= 3
Dn Slope=0.023
Boundary for River Rch & Prof#=SCLT4,SCLT4           , 1
Up Type= 0
Dn Type= 3
Dn Slope=0.0082
Boundary for River Rch & Prof#=SCLT3,SCLT3           , 1
Up Type= 0
Dn Type= 3
Dn Slope=0.016
Boundary for River Rch & Prof#=SCLT2,SCLT2           , 1
Up Type= 0
Dn Type= 3
Dn Slope=0.003
Boundary for River Rch & Prof#=SCLT2A,SCLT2A          , 1
Up Type= 0
Dn Type= 3
Dn Slope=0.0038
Boundary for River Rch & Prof#=SCLT2A1,SCLT2A1         , 1
Up Type= 0
Dn Type= 3
Dn Slope=0.016
Boundary for River Rch & Prof#=BGL,BGL             , 1
Up Type= 0
Dn Type= 3
Dn Slope=0.0076
Boundary for River Rch & Prof#=SCLT1,SCLT1           , 1
Up Type= 0
Dn Type= 3
Dn Slope=0.0025
DSS Import GetInterval= 0
DSS Import GetPeak= 0
DSS Import FillOption= 0

--- Burkes.g03 (geometry) ---

Geom Title=Existing
Program Version=3.11

River Reach=BUR             ,BUR
Reach XY= 30
 1893848.7227633  934500.0002547 1894612.2496126  935250.3794441
 1895114.7494195  936414.1893701 1895490.6301688  936178.1894232
 1895878.0007561  936647.2497443  1896668.879591  936194.2498996
 1897926.0000224  936970.5599656 1898230.3807341  936934.1892128
 1899423.2493527  937841.6301227 1900036.5007895  937628.3106679
 1900213.3806726  938351.4991214 1902238.1300304  939685.3101916
 1902124.4991036  940907.2491901 1902619.1308415  940860.5007354
 1903261.7500031  941284.0605955 1903980.3795649  940440.8799228
 1904722.2506108  941255.8099309 1905736.7493592  941084.4398259
 1906085.3806987   941653.059343 1905627.7497025  942080.4995174
 1905680.3807436  942328.8106787 1906075.6295447  942426.1895637
 1905921.7493306  942894.5006493 1906246.9997091  942952.9404152
 1906920.7503746  942412.4993029 1907095.9991328  942685.1297343
 1906938.2503511    943266.44069 1907372.5004456  943664.6307843
 1908126.1300789  943677.3098235 1909986.8800659  944703.4393699

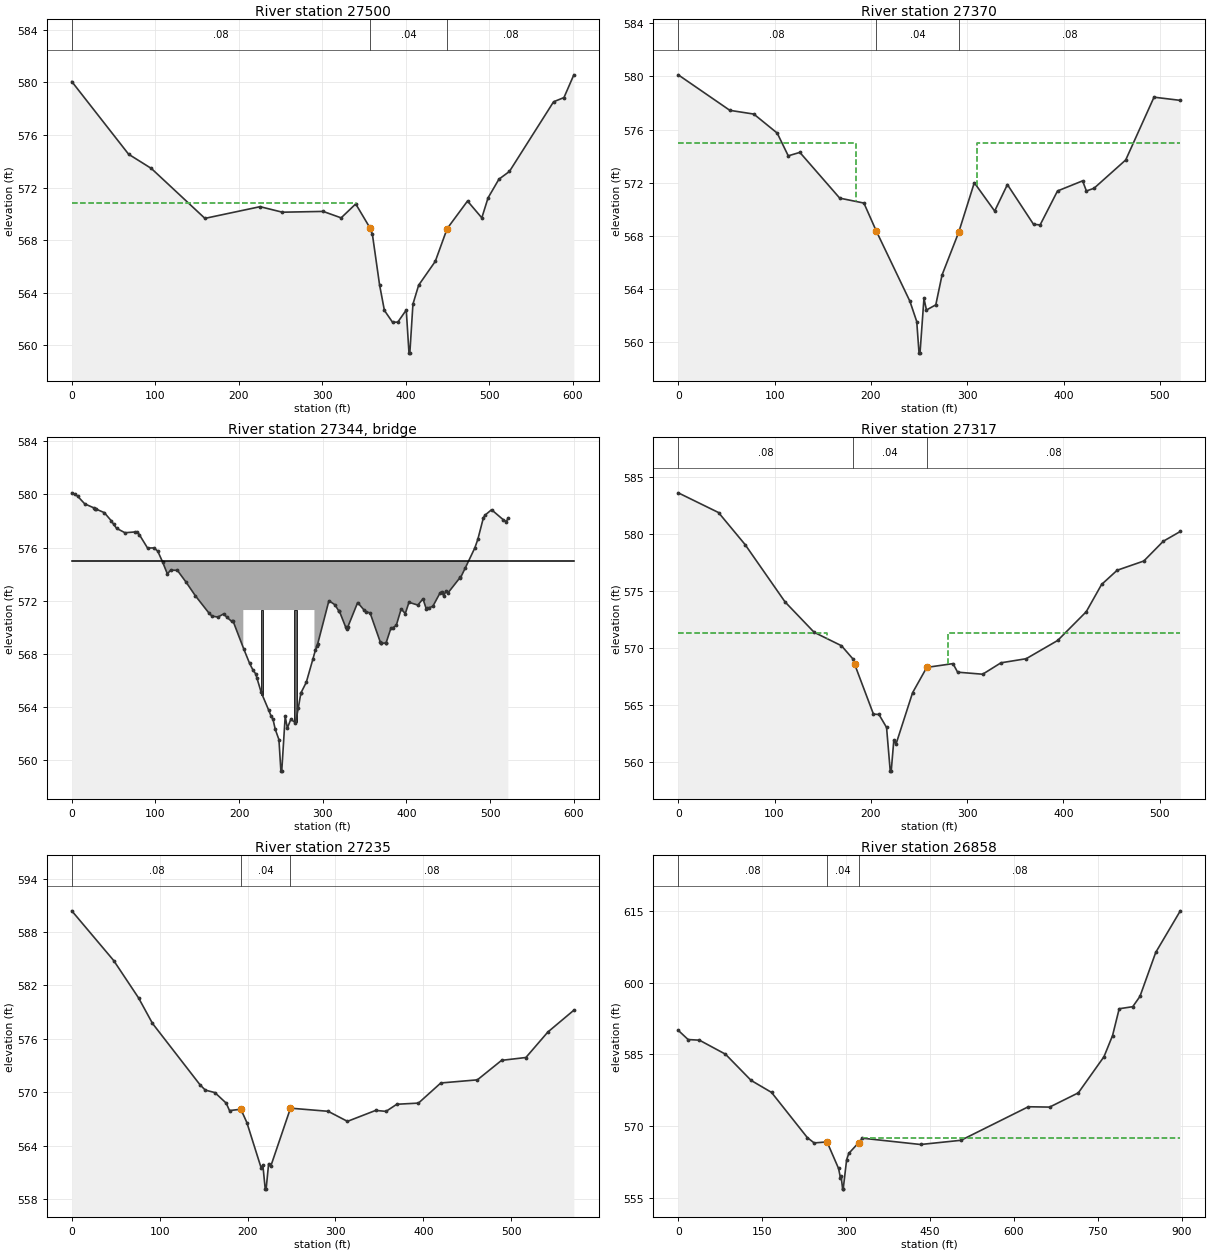
Type RM Length L Ch R = 1 ,27500   ,163,130,153
XS GIS Cut Line= 6
 1893728.2841708  934794.5848429 1893799.9623662  934605.2989414
 1893855.7005776  934511.1172251 1893925.7359607  934493.0981411
 1893960.8451338  934437.9272105 1894069.6036873  934332.1042548
#Sta/Elev= 30
       0  580.07   68.08  574.54   95.26  573.46  159.46  569.66  225.55  570.55
  252.22  570.13  301.02  570.19  322.61   569.7  340.08  570.76  357.47   568.9
  360.06  568.44  368.61  564.61  374.41  562.66  384.16  561.76  390.48  561.77
  400.59  562.69  403.87  559.41  404.87  559.41   408.6  563.14  415.44  564.58
  435.35  566.39  449.55  568.88  473.96  570.98  491.08   569.7  498.55  571.22
  511.55  572.64  524.15  573.23  577.03  578.53  589.46  578.85   601.3  580.58
#Mann= 3 , 0 , 0
       0     .08       0  357.47     .04       0  449.55     .08       0
#XS Ineff= 2 , 0
          340.14  570.82
Permanent Ineff=
       F       F
Bank Sta=357.47,449.55
XS Rating Curve= 0
Exp/Cntr=0.5,0.3

Type RM Length L Ch R = 1 ,27370   ,63,53,51
XS GIS Cut Line= 6
 1893768.1786258  934797.5400185 1893900.6600393  934648.2431386
 1893960.8451338  934583.0422191 1893979.2354242  934564.6518694
 1894012.6715878  934521.1840558 1894136.0944852  934432.5792753
#Sta/Elev= 30
       0  580.11   53.58  577.44   78.44  577.16  102.73  575.73   114.2  574.02
  126.22  574.28  167.62  570.84  192.72  570.47  205.61  568.36  240.46  563.09
  247.56  561.56  249.93  559.19  250.93  559.19  255.04   563.3  257.64  562.43
  267.33  562.82   273.8  565.06  291.08  568.27   307.3     572  328.42  569.87
  341.65  571.86   368.8  568.87  375.63  568.83  393.66  571.38  419.71  572.14
  423.64  571.38  431.51  571.58  464.44  573.71  493.82  578.43  521.12  578.19
#Mann= 3 , 0 , 0
       0     .08       0  205.61     .04       0  291.08     .08       0
#XS Ineff= 2 , 0
       0     185     575     310       0     575
Permanent Ineff=
       F       F
Bank Sta=205.61,291.08
XS Rating Curve= 0
Exp/Cntr=0.5,0.3

Type RM Length L Ch R = 3 ,27344   ,,,
Node Photo=C:\Tech Models\CountryLine\Pictures\Burkes Creek\BUR02-BR\BUR02-BR-USF.JPG
BEGIN DESCRIPTION:
Oak View Loop SR 1783
END DESCRIPTION:
Bridge Culvert--1,0,-1,-1, 0
Deck Dist Width WeirC Skew NumUp NumDn MinLoCord MaxHiCord MaxSubmerge Is_Ogee
16,20,2.6,0, 8, 8, , , 0.95, 0, 0,0,,
       0     204     205     250     290     291     400     600
     575     575     575     575     575     575     575     575
                   571.3   571.3   571.3
       0     174     175     250     260     261     400     600
     575     575     575     575     575     575     575     575
                   571.3   571.3   571.3
Pier Skew, UpSta & Num, DnSta & Num=  ,227.5, 2 ,197.5, 2 , 0 , 0 , 0 ,,
       3       3
     560   571.3
       3       3
     560   571.3
Pier Skew, UpSta & Num, DnSta & Num=  ,267.5, 2 ,237.5, 2 , 0 , 0 , 0 ,,
       3       3
     460   571.3
       3       3
     460   571.3
BR Coef=-1 , 0 , 0 ,, 0 ,,,0.8,-1,,0,
WSPro=,,,, 1 ,,,, 0 ,,,, 0 ,,,,-1 ,-1 ,-1 , 0 , 0 , 0 , 0 , 0
BR U #Sta/Elev= 100
       0  580.11    3.45  580.02    7.08  579.85   15.52  579.28   26.37  578.98
   27.68  578.91   28.59   578.9   38.89  578.62   47.47  577.99   49.95  577.75
   53.58  577.44   63.58  577.11   75.72  577.17   78.44  577.16   80.71  576.97
   90.57  575.96   98.27  575.97  102.73  575.73  108.74  574.88   114.2  574.02
  118.41   574.3  126.22  574.28  136.76  573.38  147.59  572.38  164.18  571.05
  167.62  570.84  174.69  570.77  181.55  571.01  185.57  570.74  191.08  570.45
  192.72  570.47  205.61  568.36  212.52  567.29  216.61  566.78  219.84   566.5
  221.27  566.19  226.37  565.11  235.41  563.76  238.38   563.3  240.46  563.09
  243.17  562.33  247.56  561.56  249.93  559.19  250.93  559.19  255.04   563.3
  257.64  562.43  261.81  563.09  267.33  562.82   270.7  563.93   273.8  565.06
  273.95  565.08  280.28  565.87  288.33  567.65  291.08  568.27  292.86  568.57
  293.88  568.75   307.3     572  314.34   571.7  319.22  571.22   319.8  571.21
  327.41     570  328.42  569.87  329.96  570.04  341.65  571.86  348.99  571.32
  352.06  571.16   356.5  571.08   368.8  568.87  369.18  568.85  369.96   568.8
  375.22  568.82  375.63  568.83  381.31  569.92  383.59  569.96  387.78  570.14
  393.66  571.38  398.58  571.03  402.97  571.88  413.58  571.67  419.71  572.14
  423.64  571.38  424.82  571.45  426.36  571.45  431.51  571.58  439.91  572.56
  442.06  572.68   444.5  572.34  446.92   572.7   449.5  572.58  464.15  573.75
  464.44  573.71  470.27  574.46  481.67  575.97  485.23  576.61  491.94  578.24
  493.82  578.43  501.66  578.84   515.6  578.09  519.45  577.95  521.12  578.19
BR U #Mann= 3
       0     .08  212.52    .029  288.33     .08
BR D #Sta/Elev= 85
       0  583.58   14.33  583.23   21.53  582.77      32  582.25   41.85  581.85
   47.88  581.31   69.46  579.04   80.53  577.54   86.69  576.82   90.19  576.29
   96.48  575.85  110.97  574.01  124.65  572.96  133.88  572.15  141.13  571.35
  145.88  571.23  151.69  570.95  169.52  570.17  170.87  570.02  179.53  569.13
  181.46  569.01  183.12  568.57  195.03   565.8  198.48  565.07  202.75  564.17
  208.47  564.14  209.44  564.04  216.38     563  220.21  559.17  221.21  559.17
  223.91  561.87  226.16  561.53  227.29  561.75  230.91  562.66  237.36  564.44
  243.42  566.05  253.81  567.61  258.02  568.25   258.3  568.27  265.85  568.21
  267.29  568.19  269.45  568.17  277.11  568.33  277.92  568.38  285.38   568.6
  290.17  567.85  310.95  567.75  312.98   567.7  313.42  567.68  316.21  567.67
  328.07   568.2  328.94  568.24  330.78  568.27  335.18  568.67  339.16  568.62
  352.74  568.72  361.39  569.03  368.16  569.56  370.67  569.71  377.49  570.08
  377.87  570.09  378.42  570.16   392.3  570.58  394.04  570.63  394.11  570.63
  399.68   571.3  405.59  571.65  416.05  572.54  418.01  572.71  423.78  573.15
   439.7  575.54  442.24   575.7  447.76  576.19  455.91  576.79  459.36  577.02
  461.59  577.16  465.78  576.95  467.69  576.89  482.64  577.58  483.33  577.59
  483.59   577.6  483.94  577.65  503.77  579.33  516.69  579.87  521.49  580.19
BR D #Mann= 3
       0     .08  181.46    .029  258.02     .08
BC Design=,, 0 ,, 0 ,,,,,,

Type RM Length L Ch R = 1 ,27317   ,69,82,90
XS GIS Cut Line= 6
 1893816.9385483  934822.6587736 1893932.4231341   934696.725116
 1893999.2971224  934613.1339061 1894074.8632852  934559.4133917
 1894150.8702445  934513.8458325 1894207.0180466  934487.2494896
#Sta/Elev= 30
       0  583.58   41.85  581.85   69.46  579.04  110.97  574.01  141.13  571.35
  169.52  570.17  181.46  569.01  183.12  568.57  202.75  564.17  208.47  564.14
  216.38     563  220.21  559.17  221.21  559.17  223.91  561.87  226.16  561.53
  243.42  566.05  258.02  568.25   258.3  568.27  285.38   568.6  290.17  567.85
  316.21  567.67  335.18  568.67  361.39  569.03  394.11  570.63  423.78  573.15
   439.7  575.54  455.91  576.79  483.59   577.6  503.77  579.33  521.49  580.19
#Mann= 3 ,-1 , 0
       0     .08       0  181.46     .04       0  258.02     .08       0
#XS Ineff= 2 , 0
       0     155   571.3     280       0   571.3
Permanent Ineff=
       F       F
Bank Sta=183.12,258.3
XS Rating Curve= 0
Exp/Cntr=0.5,0.3

Type RM Length L Ch R = 1 ,27235   ,394,377,353
XS GIS Cut Line= 6
 1893895.6442143  934899.0167683 1893960.8451338  934763.5991043
 1894059.4822169  934685.0237194 1894110.9327777  934626.1039423
 1894141.9262287  934590.6111041 1894288.2846038  934504.9804244
#Sta/Elev= 30
       0  590.38   47.77  584.79   75.95  580.61   91.85  577.74  145.91  570.85
  151.94  570.25  162.86  569.97  175.69  568.79   179.5  567.95  192.41   568.1
  199.23  566.61  215.54   561.5  217.42  561.86  220.15  559.13  221.15  559.13
  224.01  561.99  226.37  561.68  248.88  568.22  291.69  567.87  313.72  566.74
  345.83  567.97  357.58  567.86  369.84  568.66  394.49  568.79  419.93  571.05
  461.55   571.4  489.08  573.59  516.76  573.91  541.73  576.77  571.32  579.22
#Mann= 3 , 0 , 0
       0     .08       0  192.41     .04       0  248.88     .08       0
Bank Sta=192.41,248.88
XS Rating Curve= 0
Exp/Cntr=0.3,0.1

Type RM Length L Ch R = 1 ,26858   ,440,482,518
XS GIS Cut Line= 5
  1894171.356009  935211.2202827 1894236.2965441  935007.7393105
 1894322.8845175   934877.858181 1894448.4368239  934730.6584957
 1894509.0485358  934401.6252172
#Sta/Elev= 30
       0  590.05   17.65  588.12   37.88  587.99   84.46  585.06  130.27  579.58
  166.82  577.07  230.84  567.62  242.98  566.51  266.07  566.72  286.67  561.17
  290.03  559.22  291.18  559.62  293.95  556.85  294.95  556.85  301.09  562.99
   304.9  564.31  322.82  566.59  329.26   567.5  433.35  566.18  505.59  567.06
  625.97  574.07  664.08     574  715.38  576.98  761.28  584.54  776.59  588.96
  788.45  594.56  812.66  594.99  825.52  597.13  853.79  606.34  897.73  615.03
#Mann= 3 , 0 , 0
       0     .08       0  266.07     .04       0  322.82     .08       0
#XS Ineff= 2 , 0
                          329.25          567.52
Permanent Ineff=
       F       F
Bank Sta=266.07,322.82
XS Rating Curve= 0
Exp/Cntr=0.3,0.1

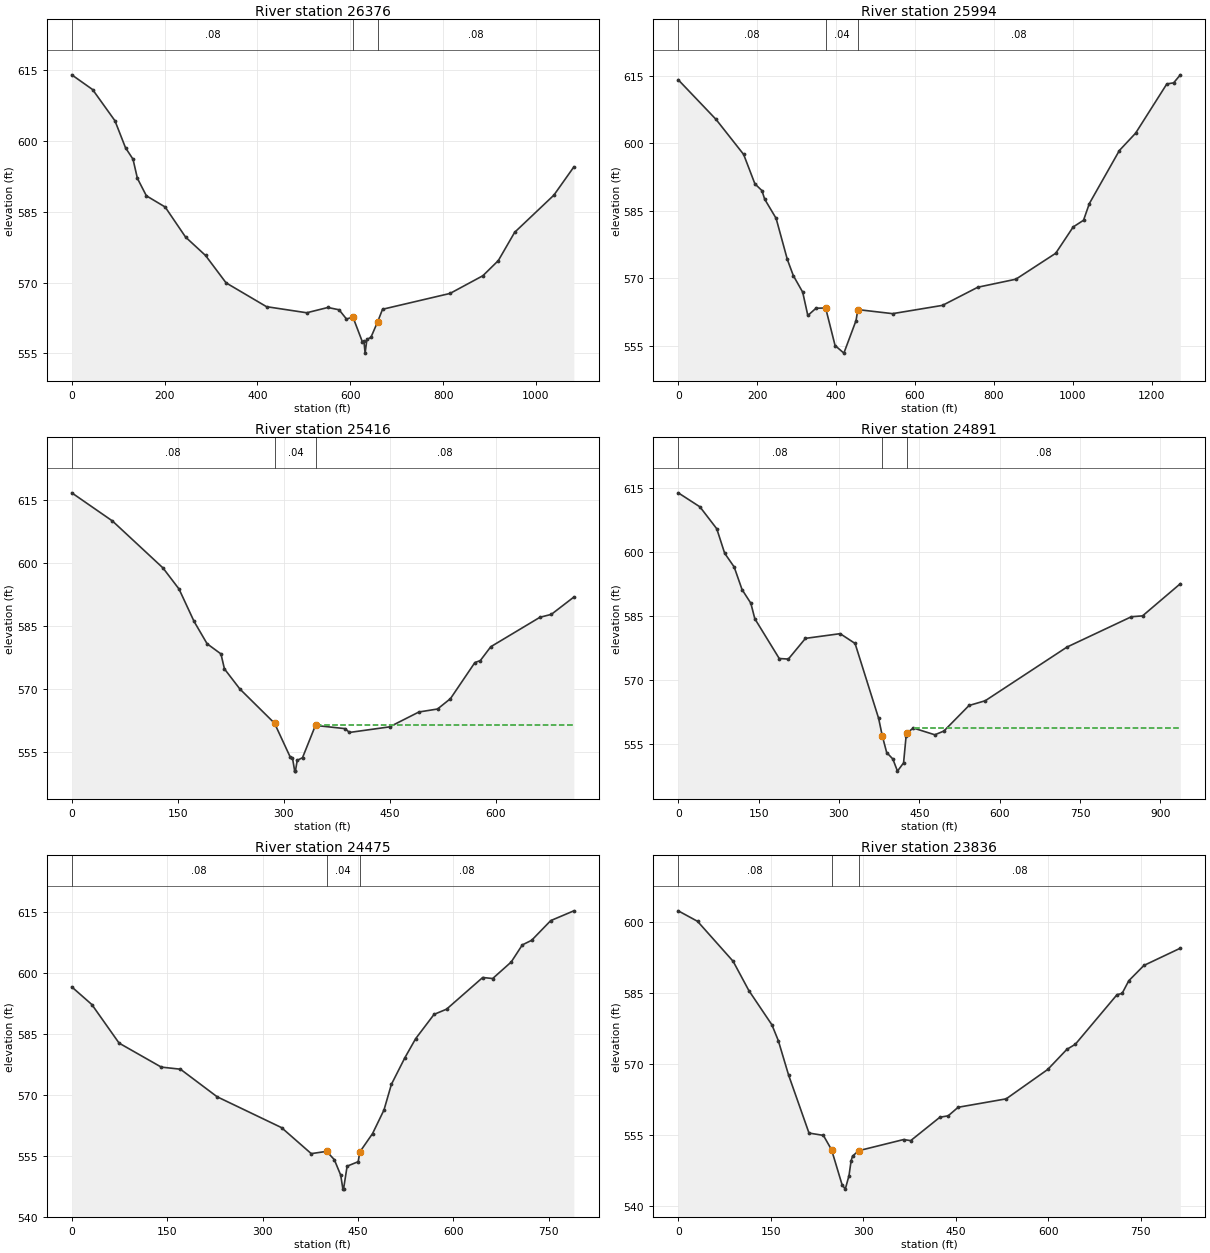
Type RM Length L Ch R = 1 ,26376   ,328,382,339
XS GIS Cut Line= 6
 1894097.7561664  935570.5602477 1894180.0153166  935445.0079414
 1894517.7078433  935323.7844583 1894742.8345333  935189.5745055
 1894786.1293506  935089.9984607 1894928.9985515  934947.1275393
#Sta/Elev= 30
       0  613.95   44.92  610.83   93.02  604.23  115.76  598.52  131.91   596.1
  141.41  592.04  160.74  588.35  201.18  585.98  245.22  579.61  288.21  575.72
  332.41  569.93  419.51  564.89  506.23   563.6  551.78  564.72  575.88  564.23
   591.8  562.28  605.71  562.69  626.08  557.44  629.38  557.61  631.93  555.06
  635.82  557.95   644.5  558.41  659.14  561.73  669.48  564.34  814.87  567.69
  885.68  571.44   918.9  574.64  954.14  580.63  1038.6  588.49 1081.62  594.46
#Mann= 3 , 0 , 0
       0     .08       0  605.71     .04       0  659.14     .08       0
Bank Sta=605.71,659.14
XS Rating Curve= 0
Exp/Cntr=0.3,0.1

Type RM Length L Ch R = 1 ,25994   ,568,578,539
XS GIS Cut Line= 5
     1894254.191     935712.1753     1894583.774     935620.3927
    1894708.9322     935591.1892    1895017.6555     935361.7326
    1895230.4243      935002.946
#Sta/Elev= 30
       0  614.14   95.88  605.33  165.79  597.55  194.32  591.02  212.19  589.52
  218.94  587.64  248.03  583.36  276.52  574.22  291.61  570.65  315.42  566.96
  328.44  561.78  349.09  563.39  373.54  563.45  397.49  555.11   419.8  553.42
  450.59  560.65  455.21  563.09   543.3  562.19  669.81  564.03  759.25  568.06
  855.65  569.84  956.64   575.6 1000.96  581.45 1027.12  582.93 1041.93  586.65
 1117.99  598.43 1159.13  602.28 1238.27  613.22 1255.59  613.46 1272.43  615.24
#Mann= 3 , 0 , 0
       0     .08       0  373.54     .04       0  455.21     .08       0
Bank Sta=373.54,455.21
XS Rating Curve= 0
Exp/Cntr=0.3,0.1

Type RM Length L Ch R = 1 ,25416   ,562,525,454
XS GIS Cut Line= 2
 1894625.9415345  936094.4151315  1895296.996163   935860.629134
#Sta/Elev= 30
       0  616.63   57.56  609.94   129.1  598.78   151.8  593.77  173.14  586.06
  191.56  580.76  211.15  578.35   216.1  574.79  237.91  570.02  286.99  561.88
  308.92  553.94  312.38  553.64  315.52   550.5  316.52   550.5  319.08  553.06
  326.58  553.69  345.04  561.43  345.91  561.34  386.74   560.6  393.08  559.69
   449.8  561.02  491.31  564.55  517.67  565.26  535.95  567.72  570.59  576.31
  578.19  576.76  593.05  580.06  662.65  587.06  678.77  587.75  710.61  591.86
#Mann= 3 ,-1 , 0
       0     .08       0  286.99     .04       0  345.91     .08       0
#XS Ineff= 2 , 0
                          345.06          561.49
Permanent Ineff=
       F       F
Bank Sta=286.99,345.04
XS Rating Curve= 0
Exp/Cntr=0.3,0.1

Type RM Length L Ch R = 1 ,24891   ,441,416,366
XS GIS Cut Line= 6
    1894850.7781     936675.8929     1895055.203     936567.4225
    1895134.4698     936504.8434    1895172.0172     936404.7169
    1895201.2208     936116.8533    1895326.3789     935949.9758
#Sta/Elev= 30
       0  613.81   40.51  610.53   71.94   605.4   86.68  599.68  104.41  596.47
  119.14  591.18  135.54  587.99  142.94  584.37  188.55  575.06  205.59  574.93
  237.52  579.77  302.32  580.87  330.13  578.58  374.12  561.05  380.89  556.98
  389.14  553.06  400.58  551.57  409.28  548.72  420.67  550.65  425.39  556.92
  427.17  557.67  438.97   558.8  479.05  557.22  495.98   558.1  542.85  564.07
   573.1  565.18  725.79  577.74  845.98  584.83   866.8  585.03  937.29  592.55
#Mann= 3 , 0 , 0
       0     .08       0  380.89     .04       0  427.17     .08       0
#XS Ineff= 2 , 0
                          439.37           558.8
Permanent Ineff=
       F       F
Bank Sta=380.89,427.17
XS Rating Curve= 0
Exp/Cntr=0.3,0.1

Type RM Length L Ch R = 1 ,24475   ,608,639,663
XS GIS Cut Line= 5
 1895379.2553132  936561.9887878 1895478.8314173  936362.8382999
 1895413.8908229  936085.7574851 1895387.9146207  936007.8271581
  1895513.466927  935851.9698264
#Sta/Elev= 30
       0  596.48   31.63  592.14   74.43  582.67  140.72  576.78   170.9  576.26
  228.57  569.49  329.87  561.91  376.58  555.52  400.79  556.08  412.86  554.04
  422.94  550.22  426.36   546.8  427.36   546.8     433  552.44  450.39  553.54
  452.93  555.92     473  560.45  490.98  566.25  502.64  572.55  523.86  579.09
  540.75  583.76  569.72  589.73  589.39  591.01   646.2  598.79  661.92  598.54
     691  602.59   708.5   606.8  723.16  607.93  753.21  612.77  789.53  615.17
#Mann= 3 , 0 , 0
       0     .08       0  400.79     .04       0  452.93     .08       0
Bank Sta=400.79,452.93
XS Rating Curve= 0
Exp/Cntr=0.3,0.1

Type RM Length L Ch R = 1 ,23836   ,483,438,399
XS GIS Cut Line= 6
    1895706.0252     936871.9739    1895772.7762     936705.0964
    1895818.6675     936659.2051     1895856.215     936571.5944
    1895827.0114     936279.5588    1895768.6043     936108.5094
#Sta/Elev= 30
       0  602.33   31.35  600.11   89.04  591.66  114.52  585.48  151.93  578.23
  162.28   574.9  178.99  567.61  212.06  555.36  235.37  554.87  248.64  551.83
  265.62  544.47  270.88  543.51  276.95  546.39  280.36  549.51  282.68  550.49
  292.54  551.63  365.51  553.99  376.98  553.76  424.33  558.71  437.74     559
  453.91  560.81  531.78  562.59  599.27  568.81  630.21  573.05  643.98  574.13
  711.57  584.61   719.8  584.87  730.65  587.56  755.21  590.79  814.19  594.43
#Mann= 3 , 0 , 0
       0     .08       0  248.64     .04       0  292.54     .08       0
Bank Sta=248.64,292.54
XS Rating Curve= 0
Exp/Cntr=0.3,0.1

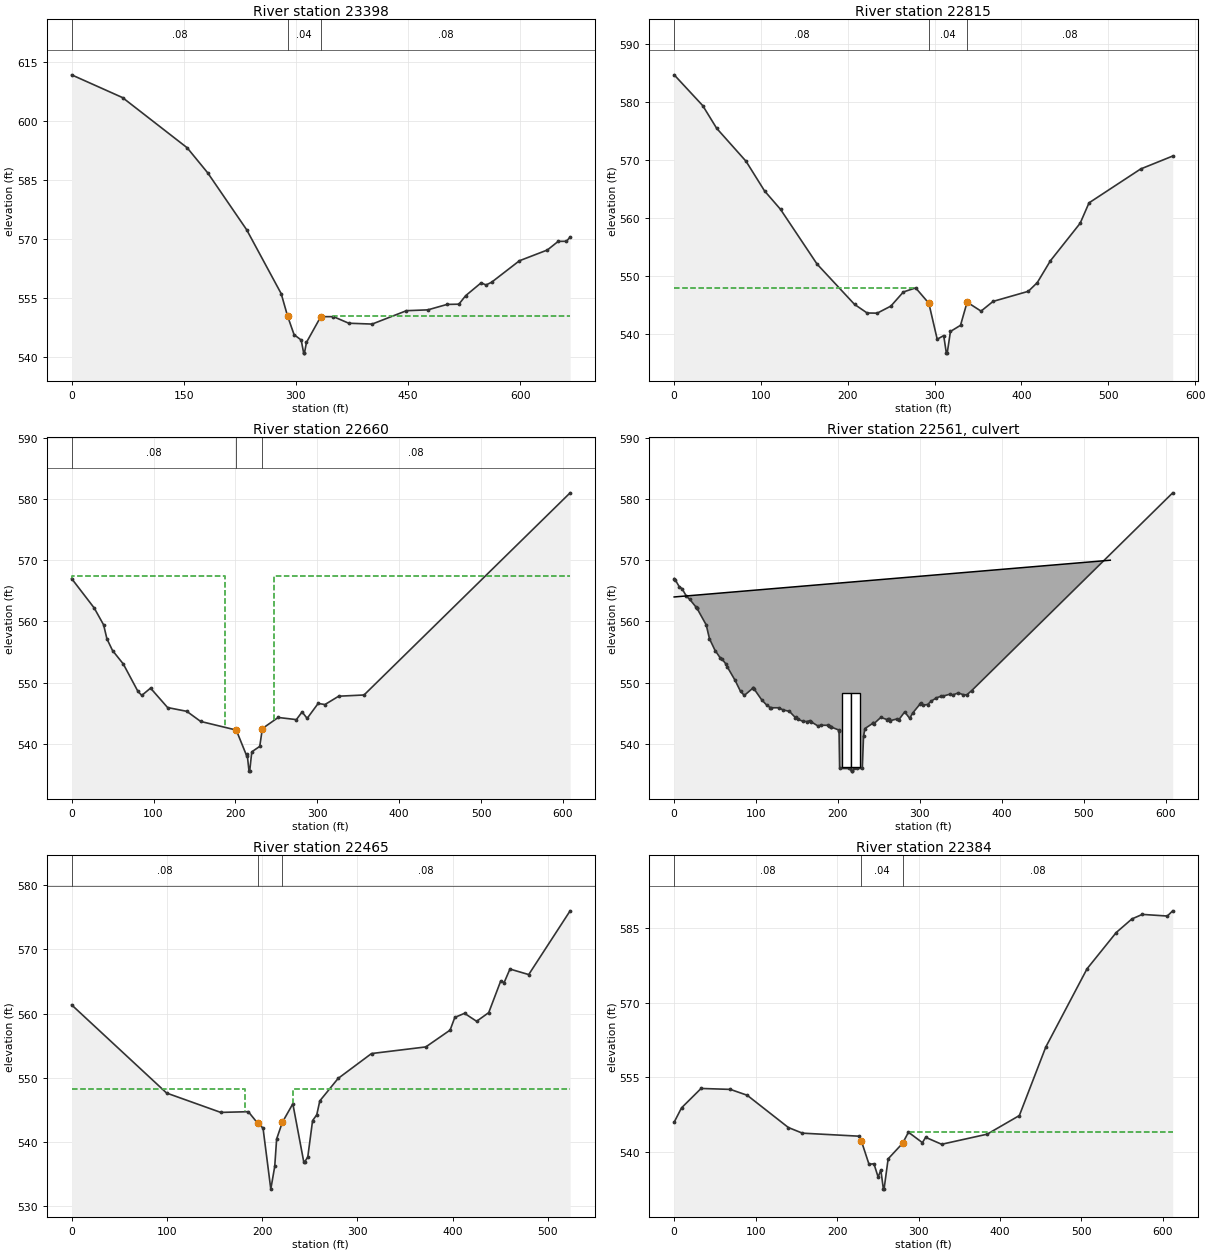
Type RM Length L Ch R = 1 ,23398   ,556,583,601
XS GIS Cut Line= 4
 1896271.1094696  936861.1504216 1896284.0976003  936627.3627035
 1896175.8622479  936462.8461236 1895985.3694065  936324.3056865
#Sta/Elev= 30
       0  611.81   68.15  606.01  154.54  593.23  182.02  586.84  234.15  572.33
  280.26  556.07  288.76  550.38  297.52  545.61     307  544.26  310.34  540.92
  311.34  540.92  314.08  543.66  332.91  550.11  333.39  550.21  350.17  550.21
  370.58  548.54  401.83  548.32   447.8  551.73  476.31  551.94  502.14  553.33
  517.86  553.39   526.9  555.55  547.62  558.83  554.15  558.28  561.57  558.97
  598.82  564.45  636.17  567.19  650.68  569.39  661.72  569.41  666.62   570.5
#Mann= 3 ,-1 , 0
       0     .08       0  288.76     .04       0  333.39     .08       0
#XS Ineff= 2 , 0
                          350.14          550.31
Permanent Ineff=
       F       F
Bank Sta=288.76,332.91
XS Rating Curve= 0
Exp/Cntr=0.3,0.1

Type RM Length L Ch R = 1 ,22815   ,165,155,145
XS GIS Cut Line= 6
 1896669.4121064  936493.1528101 1896690.8444858  936396.8371761
 1896670.8600902  936298.5881483 1896669.1954457  936206.9994781
 1896659.2040191  936093.7617086 1896530.8717286  935982.2843366
#Sta/Elev= 30
       0  584.68   32.92  579.36      49  575.44   82.83  569.75  104.11  564.64
  122.49  561.46  164.64     552  207.71  545.06  222.24  543.57  233.86  543.54
  249.59  544.76  264.02   547.2  278.17   547.9  293.33  545.25  302.96  539.04
  310.45  539.67  313.48  536.64  314.48  536.64  318.22  540.38  329.81  541.44
  337.41  545.44  353.45  543.89  367.32  545.57  407.91  547.31  418.21  548.81
  433.29  552.57  467.61  559.06  477.82  562.58  537.31  568.43   574.2  570.66
#Mann= 3 , 0 , 0
       0     .08       0  293.33     .04       0  337.41     .08       0
#XS Ineff= 2 , 0
          278.19  547.91
Permanent Ineff=
       F       F
Bank Sta=293.33,337.41
XS Rating Curve= 0
Exp/Cntr=0.5,0.3

Type RM Length L Ch R = 1 ,22660   ,205,195,191
XS GIS Cut Line= 6
 1896847.8776703  936488.4259056 1896871.1914736  936423.4819889
 1896822.8992819  936296.9217833 1896822.8992819   936270.278691
 1896814.5725592  936238.6382837 1896652.0420664  935787.8882072
#Sta/Elev= 30
       0  567.01  27.614   562.2  39.115  559.44   43.12  557.17  49.968  555.26
  63.116  553.06  81.022  548.58  85.683  547.93   96.39  549.12 117.204  545.95
 140.648  545.33  157.58  543.68  201.11  542.27 201.274  542.19 214.053  537.97
  214.29  538.39   216.6  535.57 217.419  535.57     220  538.72 229.707  539.61
 232.901  542.52 252.225  544.33 274.416  543.98 281.403  545.23  287.58  544.18
 301.014  546.62 309.304  546.44 326.088   547.8 357.027     548  608.63     581
#Mann= 3 ,-1 , 0
       0     .08       0 201.274     .04       0 232.901     .08       0
#XS Ineff= 2 , 0
       0 187.586   567.4 247.384       0   567.4
Permanent Ineff=
       F       F
Bank Sta=201.11,232.901
XS Rating Curve= 0
Skew Angle= 35
Exp/Cntr=0.5,0.3

Type RM Length L Ch R = 2 ,22561   ,,,
Node Photo=C:\Tech Models\CountryLine\Pictures\Burkes Creek\BUR01-CUL\BUR01-CUL-USF.JPG
BEGIN DESCRIPTION:
US 62
END DESCRIPTION:
Bridge Culvert--1,0,-1,-1, 0
Deck Dist Width WeirC Skew NumUp NumDn MinLoCord MaxHiCord MaxSubmerge Is_Ogee
23,146,2.6,35, 2, 2, , , 0.95, 0, 0,0,,
       0 532.449
     564     570
                
       0 523.438
     564     576
                
BR Coef=-1 , 0 , 0 ,, 0 ,,,0.8,-1,,0,
WSPro=,,,, 1 ,,,, 0 ,,,, 0 ,,,,-1 ,-1 ,-1 , 0 , 0 , 0 , 0 , 0
Culvert=2,12,11,146,0.013,0.4,1,8,1,536.3,210,536.3,202,Culvert #1  , 0 ,23
Culvert Bottom n=0.03
Culvert=2,12,11,146,0.013,0.4,1,8,1,536.3,221.5,536.3,213.5,Culvert #2  , 0 ,23
Culvert Bottom n=0.03
BR U #Sta/Elev= 82
       0  567.01   1.049  566.85   6.135   565.7   9.609  565.36  14.999  564.11
  19.053   563.6  26.803  562.33   27.27  562.27  27.614   562.2  39.115  559.44
   43.12  557.17  49.968  555.26  56.521     554  58.102  553.92  63.116  553.06
  64.901  552.57  74.371  550.39  81.022  548.58  85.683  547.93  95.988   549.1
   96.39  549.12   97.43  549.01 106.817  547.21 113.297   546.3 117.204  545.95
 118.703  545.91 127.788  545.91 133.096  545.55 140.648  545.33 147.996  544.31
 148.905  544.34 151.297  544.02  157.58  543.68 162.438  543.67 165.788  543.81
 167.484   543.6 175.421  542.95  178.87  543.06 187.242  543.05 189.314  542.99
 191.002  542.84 191.731  542.77  201.11  542.27 201.274  542.19     202     536
 214.053     536  214.29     536   216.6  535.57 217.419  535.57     220     536
 223.612     536 229.707     536 231.173  541.23 232.901  542.52 242.363  543.36
 242.821  543.38 244.034  543.33 252.225  544.33 260.327  543.97 261.457  544.01
 261.826  544.03 263.538   543.8 271.672  544.07 274.416  543.98 281.403  545.23
  287.58  544.18  291.34  545.07 300.236  546.53 301.014  546.62 303.422  546.33
 309.304  546.44 314.096  547.01 320.116  547.53 326.088   547.8 328.062   547.8
 336.934  548.14 339.899     548 346.903  548.33 352.825  548.05 357.027     548
 363.065  548.69  608.63     581
BR U #Mann= 3
       0     .08 201.274    .029 232.901     .08
BR D #Sta/Elev= 113
       0  561.37   4.325  560.84   9.306  559.82  15.392  559.03  26.098  557.64
  27.032  557.56  27.294  557.51  34.937  556.23  43.825  554.77  44.537  554.66
  45.406  554.56  54.048  553.62  57.693  553.12  63.566  552.27   70.93  551.34
  71.438  551.27  82.054  549.48   84.07  549.19  85.085  549.08  93.858  548.21
  99.797  547.64   103.5  547.48 110.807  546.62 113.575  546.57 114.272  546.49
 124.839  546.63 128.369  546.23 136.118  546.22  142.36   545.7 147.308  545.85
 155.639  544.75 156.589  544.63 156.737  544.63 158.891   544.6 168.754  544.52
 169.933  544.57 170.621  544.49 179.558  544.39 185.571  544.74   189.2  544.34
 195.343  542.95     196     536  199.93     536 200.987     536 202.027     536
 206.664   535.1 207.123  535.18 209.162  532.69 209.981  532.69 212.816  536.15
 213.291  536.23 215.281     536     220     536 221.253  543.08 223.801  544.24
 232.295  545.97 236.366  542.45 237.358  541.59 243.853  536.86 244.894  536.97
 245.336  537.15 247.974  537.68 253.036  543.36  257.41  544.25 260.605  546.42
 264.562   546.9 269.747  547.84 272.253  548.38 279.855  549.92 287.481  550.12
 290.078   550.5 295.444  550.81 299.752  551.89 304.241  552.76 304.536  552.82
 308.714  553.29 314.907  553.79  318.38  553.94 319.568  553.93 328.996  553.75
 334.001  553.75 339.678   554.2  348.09  554.77 350.147  555.18 356.503  554.85
 361.131   554.9 367.734  554.72 371.911  554.82  374.86  554.98 382.208  555.91
 384.403  555.94 392.259  557.61 397.428  557.44 402.343  559.41 410.371  559.44
 412.566  560.05 420.332  558.82 422.617  558.96 425.255  558.81 431.767     560
 437.976  560.16 441.138  560.99 442.039  560.99 450.558  565.08 454.154  564.84
 460.249  566.94 466.622  566.06 470.128  566.26 479.261  566.04 479.949  566.08
  482.44  566.73 486.142  568.24 523.438     576
BR D #Mann= 3
       0     .08 195.343    .029 221.253     .08
BC Design=,, 0 ,, 0 ,,,,,,

Type RM Length L Ch R = 1 ,22465   ,83,81,81
XS GIS Cut Line= 6
 1897055.5345811  936585.0119501 1897022.2294699  936505.0792918
 1896995.5847165  936405.1638989 1896970.6062688  936308.5795155
 1896937.3011576  936233.6425704 1896850.9898797   935980.730532
#Sta/Elev= 30
       0  561.37  99.797  547.64 156.589  544.63 185.571  544.74 195.343  542.95
 200.987   542.2 209.162  532.69 213.291  536.23 215.281  540.49 221.253  543.08
 232.295  545.97 243.853  536.86 244.894  536.97 247.974  537.68 253.036  543.36
  257.41  544.25 260.605  546.42 279.855  549.92 314.907  553.79 371.911  554.82
 397.428  557.44 402.343  559.41 412.566  560.05 425.255  558.81 437.976  560.16
 450.558  565.08 454.154  564.84 460.249  566.94 479.949  566.08 523.438     576
#Mann= 3 , 0 , 0
       0     .08       0 195.343     .04       0 221.253     .08       0
#XS Ineff= 2 , 0
       0 181.852   548.3 232.295       0   548.3
Permanent Ineff=
       F       F
Bank Sta=195.343,221.253
XS Rating Curve= 0
Skew Angle= 35
Exp/Cntr=0.5,0.3

Type RM Length L Ch R = 1 ,22384   ,440,485,512
XS GIS Cut Line= 2
 1897140.6460346  936668.4032888 1896930.5651584  935951.3897237
#Sta/Elev= 30
       0  545.94   9.035  548.83  33.036  552.74  68.981  552.55  89.648  551.37
 140.173  544.87 157.441  543.73 226.946  543.12  229.84  542.15 239.192  537.46
 245.287  537.56 250.423  534.86   253.7  536.32  256.87  532.45 257.689  532.45
 262.686  538.55  280.49   541.7 287.612  543.92 304.733  541.82 308.771  542.89
 328.382  541.49 384.182  543.52  423.78  547.28  456.21  561.08 506.883  576.86
 542.729  584.17 561.987  586.91 574.766  587.82 605.443  587.49 612.038  588.54
#Mann= 3 , 0 , 0
       0     .08       0  229.84     .04       0  280.49     .08       0
#XS Ineff= 2 , 0
                          289.41          543.91
Permanent Ineff=
       F       F
Bank Sta=229.84,280.49
XS Rating Curve= 0
Skew Angle= 35
Exp/Cntr=0.3,0.1