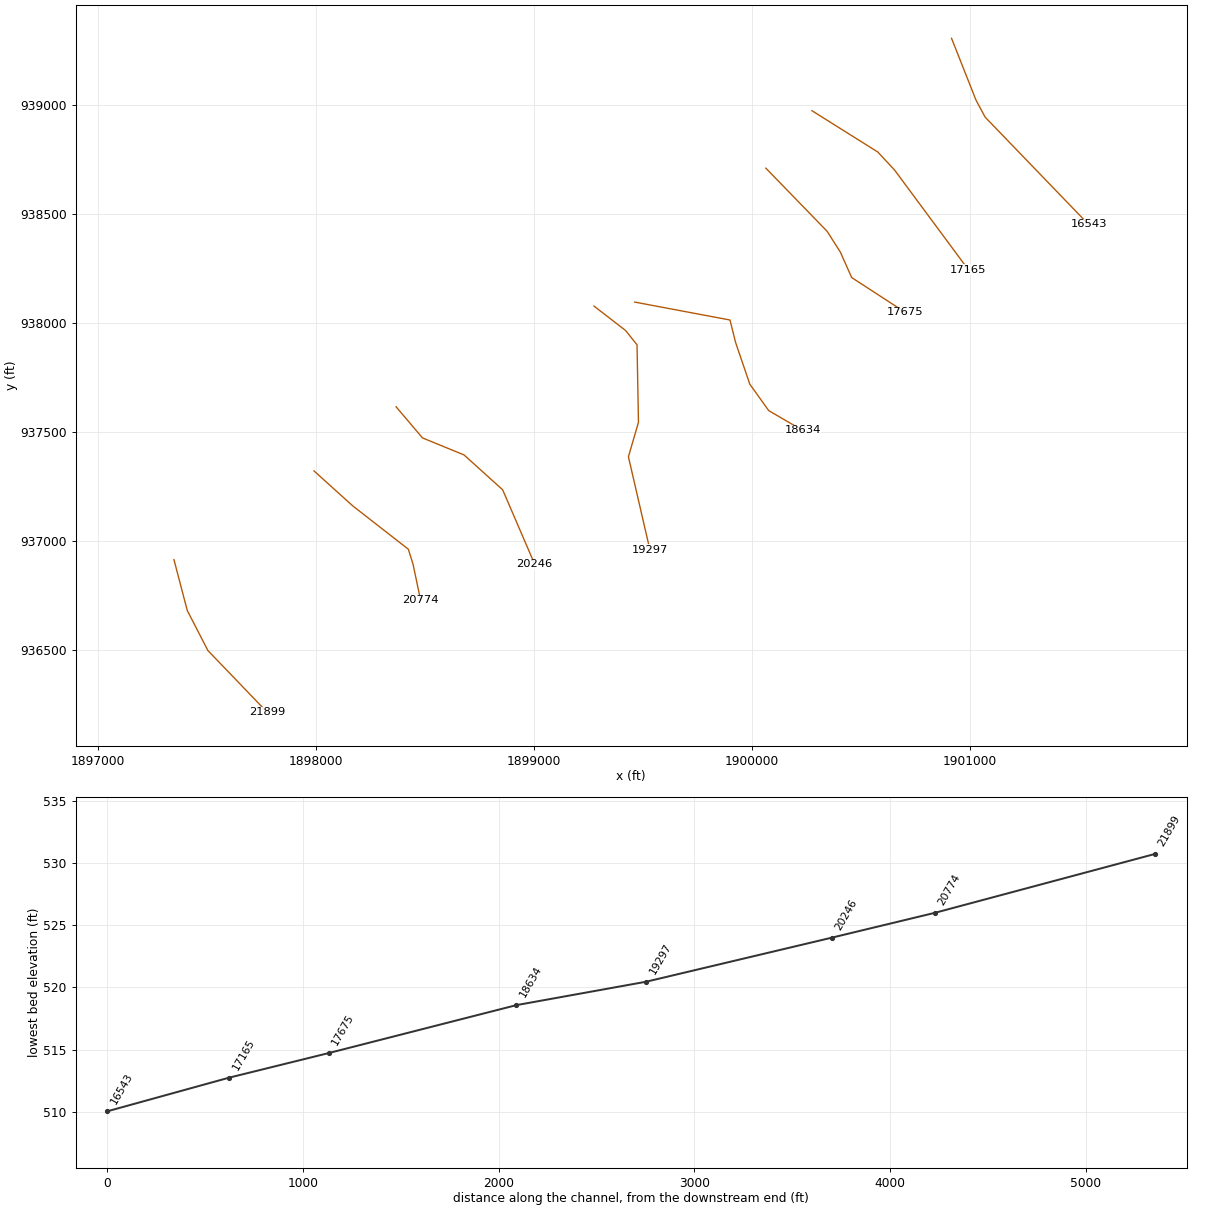
HEC-RAS study Burkes.prj: Burkes Creek

--- Burkes.g03 (geometry) --- (continued)

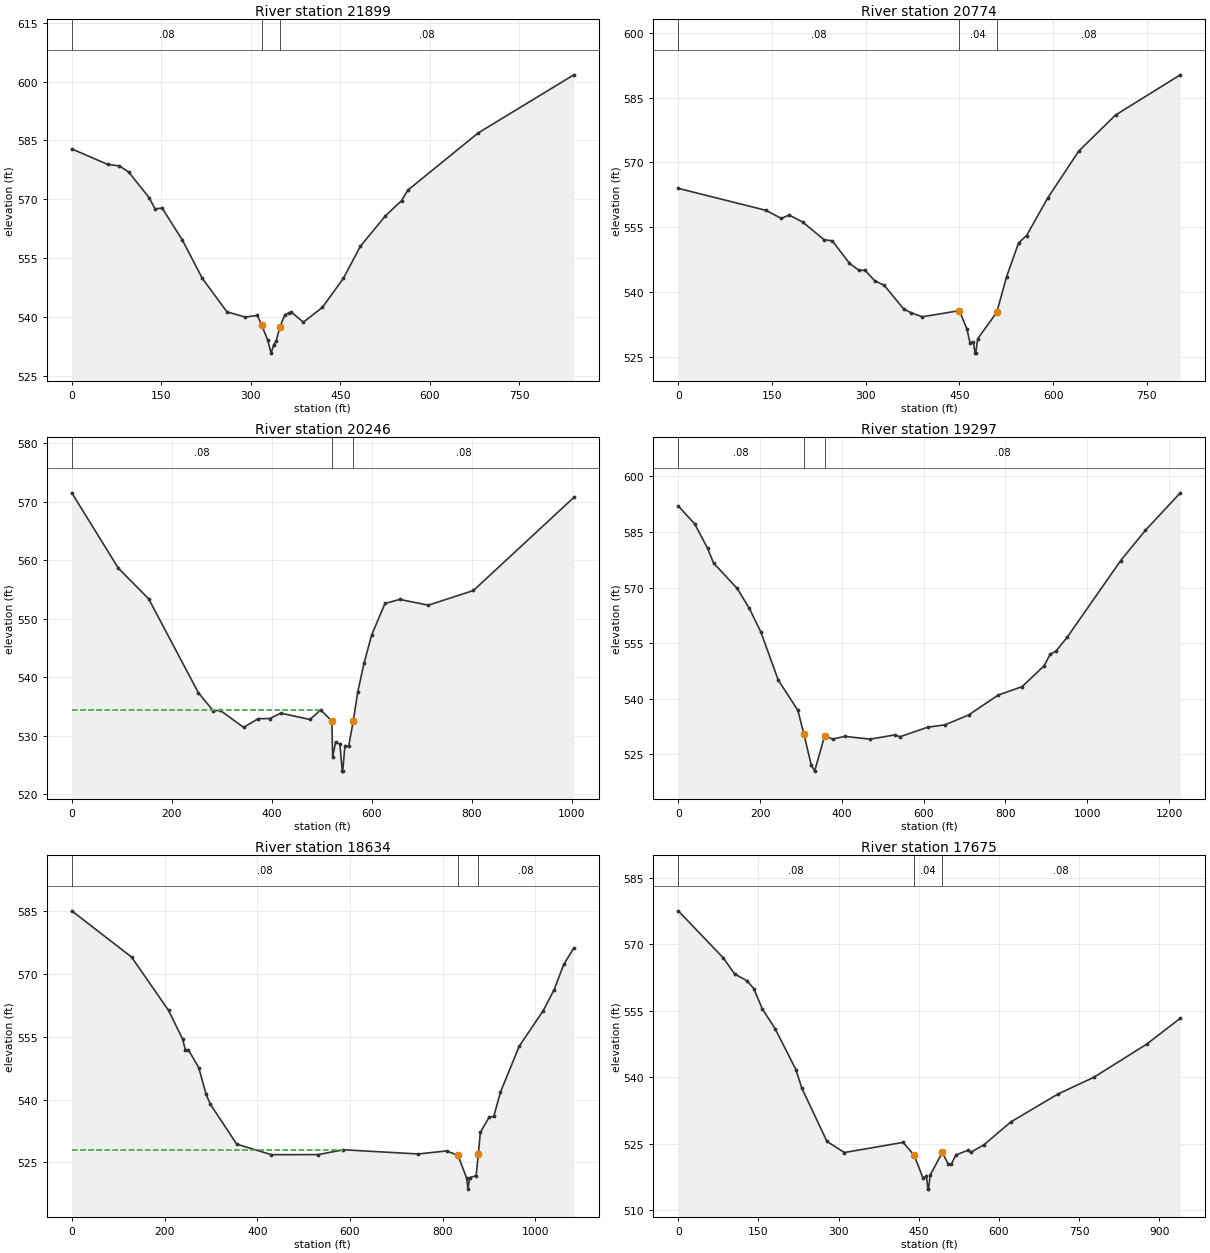
Type RM Length L Ch R = 1 ,21899   ,1029,1125,1147
XS GIS Cut Line= 4
    1897346.9872      936912.998    1897408.1756     936679.3695
    1897502.7395     936495.8042    1897775.3061     936212.1125
#Sta/Elev= 30
       0  582.83   60.27  578.86   79.69   578.5   95.13  576.97  129.73  570.38
  139.47  567.54  151.53  567.72  185.54  559.52   218.7  549.82  260.08  541.25
  290.58  539.92  311.15  540.33  318.22  537.86  328.32  534.08  334.04  530.72
  338.61  532.92  342.28  533.69  348.79  537.39  356.88  540.43  363.41     541
   368.1  541.15  388.13  538.62  419.99  542.39   455.1  549.77  483.67  557.99
  525.42  565.71  552.75  569.64  563.09  572.29  681.13   586.9  841.41  601.73
#Mann= 3 , 0 , 0
       0     .08       0  318.22     .04       0  348.79     .08       0
#XS Ineff= 2 , 0
                           368.1          541.15
Permanent Ineff=
       F       F
Bank Sta=318.22,348.79
XS Rating Curve= 0
Exp/Cntr=0.3,0.1

Type RM Length L Ch R = 1 ,20774   ,535,528,524
XS GIS Cut Line= 5
 1897989.8755861  937320.0647703 1898167.3803561  937159.8769542
 1898422.8137326  936960.7264664 1898444.4611709   936891.455447
 1898479.0966807  936726.9388077
#Sta/Elev= 30
       0  564.03   140.8  558.94  164.92  557.09  177.45  557.87  199.12  556.26
  233.38  552.19   246.6  551.92  274.06  546.74  289.29   545.1  298.85  545.12
  314.34  542.73  329.87  541.62  360.73   536.2  373.05  535.29  390.91  534.38
  450.09   535.8  462.06   531.6  466.99  528.41  472.46  528.62  475.09  525.99
  476.09  525.99  479.42  529.32  509.85   535.4  525.72  543.68  544.85  551.45
  557.63  553.13   591.7  561.87  641.23  572.65  700.04  580.96  803.69  590.24
#Mann= 3 ,-1 , 0
       0     .08       0  450.09     .04       0  509.85     .08       0
Bank Sta=450.09,509.85
XS Rating Curve= 0
Exp/Cntr=0.3,0.1

Type RM Length L Ch R = 1 ,20246   ,1017,949,885
XS GIS Cut Line= 5
 1898366.5325051  937614.4641409 1898487.7543271  937471.5932788
 1898678.2471685  937393.6646129 1898855.7518792  937233.4767969
 1899002.9515645   936891.455447
#Sta/Elev= 30
       0  571.56   93.25  558.67   153.9  553.44  253.26   537.4  282.95  534.32
  297.36  534.36  343.86  531.47  373.11  532.96  396.18  532.97   418.1   533.9
  476.61  532.82  497.97  534.46  520.17  532.58  520.37  532.44  522.05  526.47
  527.89   528.9  536.56  528.63   541.2  523.99   542.2  523.99  546.57  528.36
  553.96   528.2  563.23  532.55  572.16  537.48  584.71  542.41  600.04  547.25
  626.76  552.65  656.29  553.34  713.64  552.36  803.82  554.87 1004.64  570.78
#Mann= 3 , 0 , 0
       0     .08       0  520.17     .04       0  563.23     .08       0
#XS Ineff= 2 , 0
          497.85  534.46
Permanent Ineff=
       F       F
Bank Sta=520.17,563.23
XS Rating Curve= 0
Exp/Cntr=0.3,0.1

Type RM Length L Ch R = 1 ,19297   ,638,663,672
XS GIS Cut Line= 6
    1899274.8648     938076.7848    1899419.7739     937964.8095
    1899472.4681     937898.9418    1899479.0549     937543.2558
    1899432.9475     937385.1731    1899531.7491     936957.0326
#Sta/Elev= 30
       0  592.03   40.34  587.17   71.63  580.62   86.34  576.63  143.97  569.78
  173.44  564.47  202.19  557.94   244.6     545  292.33   536.9  307.16  530.48
  324.88  522.23  333.41  520.45  357.88  529.95  377.14  529.11  407.26  529.83
  469.11  529.08  529.35  530.23   542.4  529.74  609.82   532.3  652.24  532.95
  709.68  535.59  781.82  540.96  840.65  543.25  894.48  548.89  909.01  551.94
  923.69  552.88  950.55  556.55 1081.52  577.27 1142.15  585.46 1227.41  595.57
#Mann= 3 , 0 , 0
       0     .08       0  307.16     .04       0  357.88     .08       0
Bank Sta=307.16,357.88
XS Rating Curve= 0
Exp/Cntr=0.3,0.1

Type RM Length L Ch R = 1 ,18634   ,923,959,956
XS GIS Cut Line= 6
 1899461.8659725  938095.0259279 1899899.1346034  938012.7667777
 1899925.1108056  937908.8619097 1899990.0513407  937718.3690682
 1900076.6393141  937597.1455851 1900232.4983069  937506.2287885
#Sta/Elev= 30
       0  585.14  128.88  574.09   208.7  561.32  239.15  554.43  244.71  551.96
  251.68  551.87   273.8  547.61  289.82  541.22   298.8  538.89  355.65  529.34
  430.31  526.81  531.04  526.83  585.97  527.98  747.37  526.98  808.34  527.71
  832.84  526.66  851.77  521.13  854.33  518.57  858.07  521.31  871.99  521.81
  876.81  527.01     881  532.13  899.75  535.72  910.06  535.99  924.48  541.78
  964.86  552.73 1016.78  561.29 1040.34   566.3 1060.87  572.31 1082.71  576.26
#Mann= 3 , 0 , 0
       0     .08       0  832.84     .04       0  876.81     .08       0
#XS Ineff= 2 , 0
          585.93     528
Permanent Ineff=
       F       F
Bank Sta=832.84,876.81
XS Rating Curve= 0
Exp/Cntr=0.3,0.1

Type RM Length L Ch R = 1 ,17675   ,489,510,529
XS GIS Cut Line= 5
 1900063.6511833  938709.7976083 1900345.0608213  938419.7287221
 1900405.6725926  938324.4831023 1900457.6249969  938207.5901035
 1900704.4007864  938047.4022874
#Sta/Elev= 30
       0  577.59   84.31  566.95  105.62  563.31  128.36  561.81  141.27  560.04
  157.09  555.48  181.42  550.92  220.02  541.74   231.1  537.56   278.2  525.49
  310.79  522.99  420.72  525.28   441.3  522.38  457.63  517.28  464.23  517.59
   467.1  514.72   468.1  514.72  471.27  517.89   493.9  523.01  505.03   520.4
     511  520.37  519.17  522.44  542.87  523.54  546.77  523.03  571.51  524.71
  622.04  529.89  710.32  536.21  777.48  539.99   876.1  547.46  939.16  553.32
#Mann= 3 , 0 , 0
       0     .08       0   441.3     .04       0   493.9     .08       0
#XS Ineff= 2 , 0
          420.78  525.26
Permanent Ineff=
       F       F
Bank Sta=441.3,493.9
XS Rating Curve= 0
Exp/Cntr=0.3,0.1

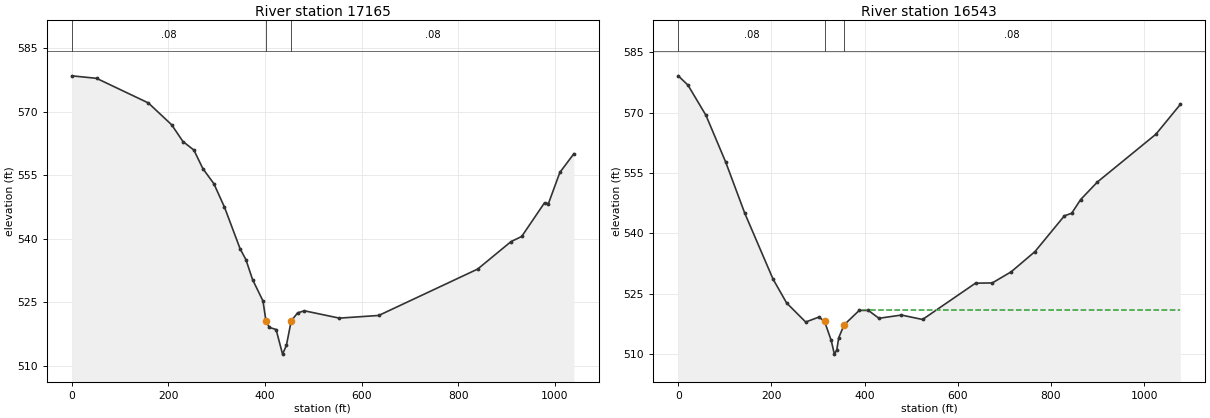
Type RM Length L Ch R = 1 ,17165   ,598,622,615
XS GIS Cut Line= 4
     1900275.131     938973.5642    1900577.7355     938783.6947
      1900654.87     938700.6268     1900993.075     938243.7533
#Sta/Elev= 30
       0  578.52    51.3  577.93  158.49  572.11   206.7  566.95  230.15  562.98
  252.79  560.97  271.32  556.58  294.06  553.03     316  547.49  348.28  537.67
  360.43  535.06  374.11  530.37  395.68  525.31  401.87   520.6  409.01  519.05
  422.85  518.56  436.19  512.74  444.11  514.78  454.19  520.61  467.47   522.5
  481.46  522.98  553.69  521.25  635.28  521.88  839.91  532.84  908.95  539.33
  931.11  540.55  978.34  548.51  986.49  548.34 1010.09  555.69 1039.03   560.1
#Mann= 3 , 0 , 0
       0     .08       0  401.87     .04       0  454.19     .08       0
#XS Ineff= 2 , 0
                          481.46          522.98
Permanent Ineff=
       F       F
Bank Sta=401.87,454.19
XS Rating Curve= 0
Exp/Cntr=0.3,0.1

Type RM Length L Ch R = 1 ,16543   ,759,799,756
XS GIS Cut Line= 4
    1900915.9406     939305.8358    1901028.6755     939021.0315
    1901070.2095     938943.8971    1901544.8833     938451.4231
#Sta/Elev= 30
       0  579.14   20.86  576.84   59.66   569.3  101.93  557.71  142.84  545.03
  203.45  528.69  232.59  522.76  273.64  518.01  302.04  519.24  314.13  518.17
  328.48  513.43  335.15  510.04  340.39  511.08  344.55  514.12  356.15  517.31
  388.59   520.9  408.22  520.89  430.88  518.94  479.23  519.74  524.53  518.64
  638.23  527.66   674.3  527.72  714.78  530.48  765.88   535.5  829.12  544.39
  844.65  545.01  863.86  548.41  899.92  552.78 1025.47  564.64  1077.9  572.04
#Mann= 3 , 0 , 0
       0     .08       0  314.13     .04       0  356.15     .08       0
#XS Ineff= 2 , 0
                          394.03          520.98
Permanent Ineff=
       F       F
Bank Sta=314.13,356.15
XS Rating Curve= 0
Exp/Cntr=0.3,0.1