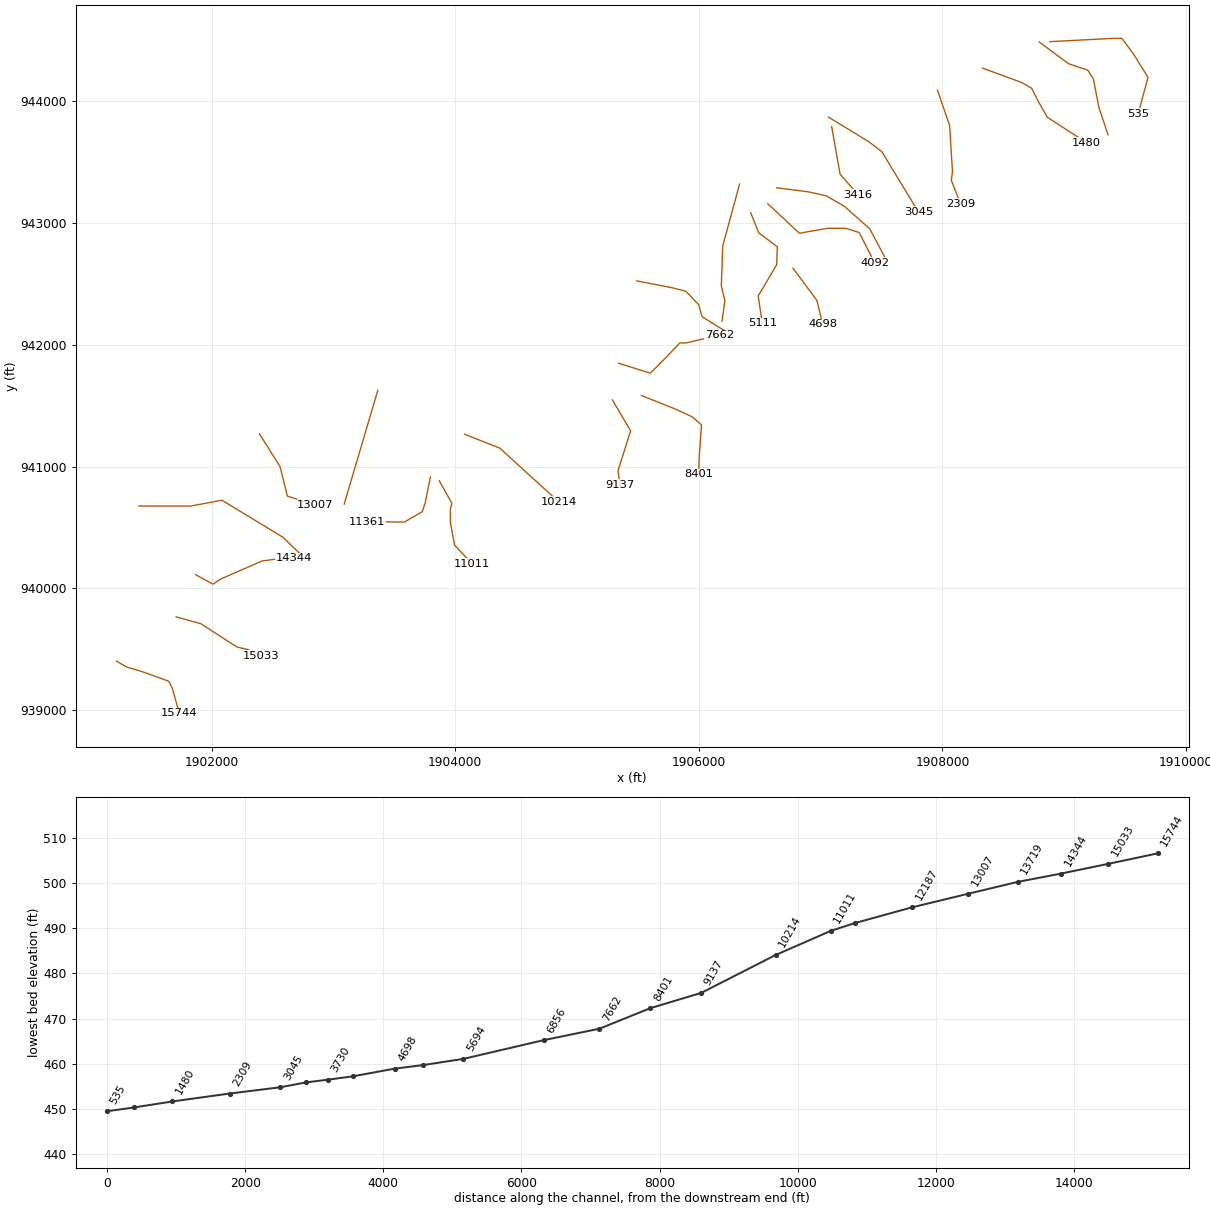
HEC-RAS study Burkes.prj: Burkes Creek

--- Burkes.g03 (geometry) --- (continued)

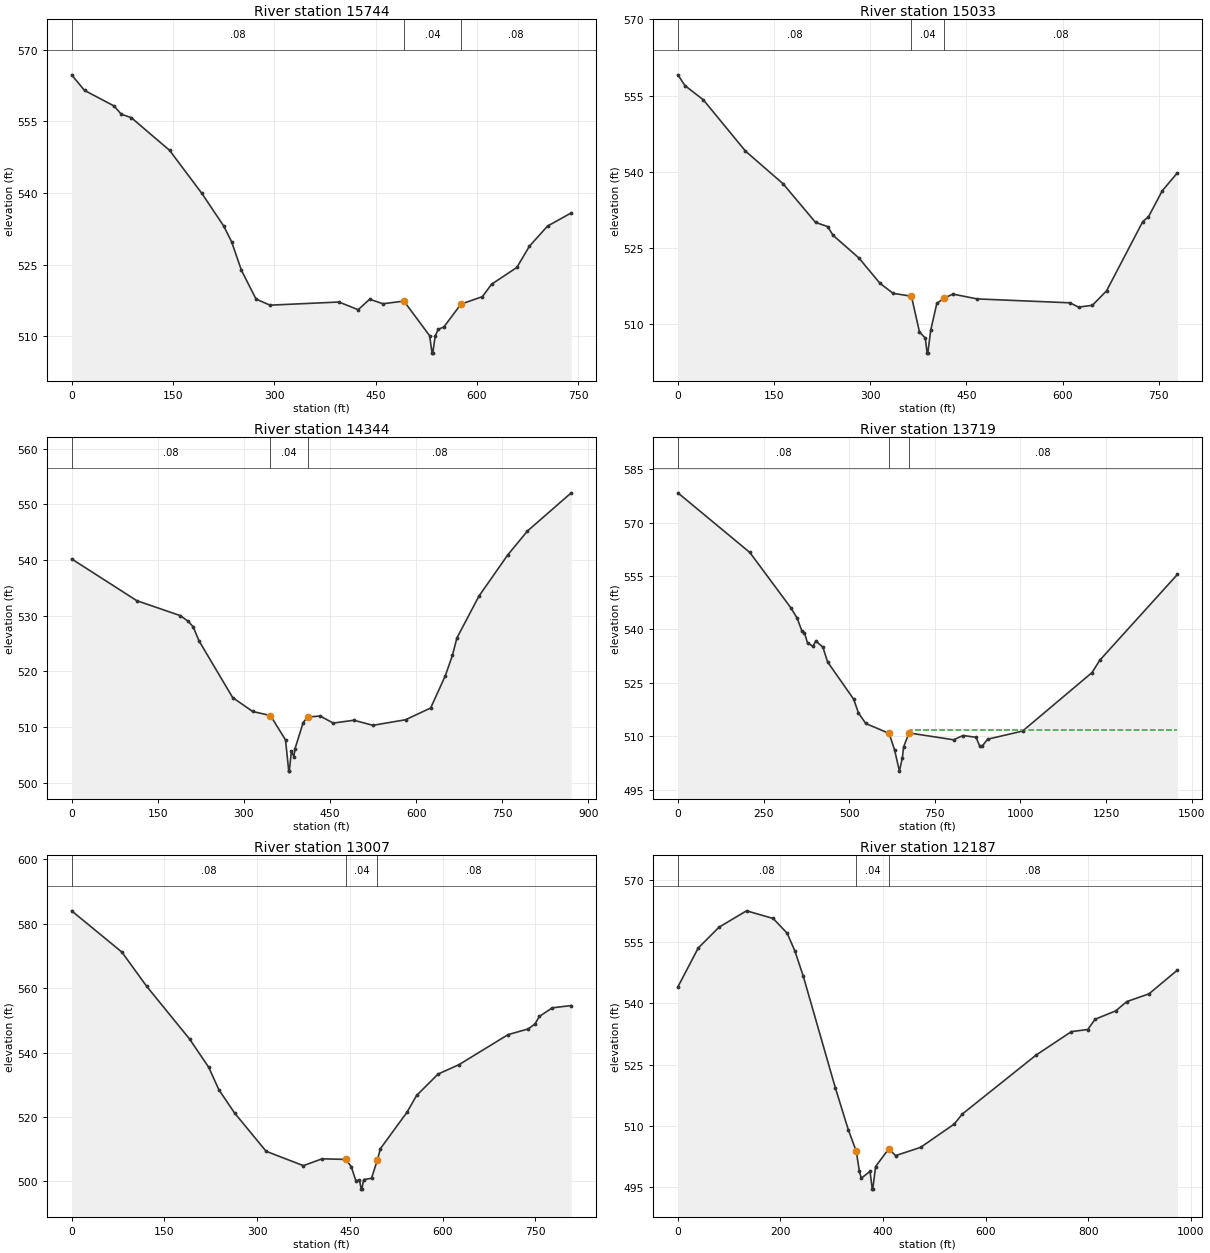
Type RM Length L Ch R = 1 ,15744   ,670,711,752
XS GIS Cut Line= 6
 1901219.5980831  939402.4996751 1901301.8555722  939354.8760346
 1901431.7383628  939315.9117017 1901648.2074064  939237.9830358
 1901678.5124318  939177.3712646 1901734.7953798  938973.8902924
#Sta/Elev= 30
       0  564.72   19.04  561.46   62.79  558.21   73.44  556.49   88.23  555.77
  145.06  548.92  192.81  539.92  225.22  533.08  236.72  529.84  251.38  523.84
  272.99  517.83  293.69  516.55  395.66  517.21  424.16   515.6  441.28   517.8
  460.72  516.84  491.91  517.41  529.97  510.16  533.61  506.52  534.61  506.52
  538.13  510.04  542.65  511.48  551.12     512  576.31  516.76  608.18  518.34
   621.7  520.93  659.14  524.44  677.79   528.9  704.53  533.09  739.62  535.84
#Mann= 3 , 0 , 0
       0     .08       0  491.91     .04       0  576.31     .08       0
Bank Sta=491.91,576.31
XS Rating Curve= 0
Exp/Cntr=0.3,0.1

Type RM Length L Ch R = 1 ,15033   ,652,689,752
XS GIS Cut Line= 5
 1901708.8191777   939766.168404 1901912.3000905  939709.8871764
 1902206.6978593  939519.3926145 1902297.6145966  939497.7468967
 1902410.1787722  939445.7944923
#Sta/Elev= 30
       0  559.09    11.1  556.96   39.66  554.17  105.45  544.05  164.11  537.61
  214.76  529.99  233.54  529.18  241.95  527.46  282.43  522.97  315.12     518
  335.71  516.01   363.9  515.45  364.28  515.44  376.81   508.4  385.87  507.17
  388.82  504.22  389.82  504.22  394.31  508.71  403.85  514.01  414.74  515.03
  428.97  515.86  466.69  514.91  611.55  514.14  624.88  513.29  646.52  513.65
  668.65  516.51  725.12  530.16  733.93  531.09  755.61  536.25  779.21  539.78
#Mann= 3 ,-1 , 0
       0     .08       0  364.28     .04       0  414.74     .08       0
#XS Ineff= 2 , 0
                          428.97          515.86
Permanent Ineff=
       F       F
Bank Sta=363.9,414.74
XS Rating Curve= 0
Exp/Cntr=0.3,0.1

Type RM Length L Ch R = 1 ,14344   ,632,625,526
XS GIS Cut Line= 6
 1901869.0052732  940112.5185771 1902011.8761947  940034.5899112
 1902076.8167298  940077.8847285 1902414.5075954  940225.0827527
 1902509.7548763  940238.0708834 1902674.2715156   940246.730191
#Sta/Elev= 30
       0  540.17  113.61  532.66  189.07  529.99  202.52     529  211.72  527.97
  221.73  525.47  280.44  515.26  315.22  512.77  346.23  512.03   372.5  507.65
   378.1  502.05   379.1  502.05  382.65   505.6  386.98  504.66  388.93  506.07
   403.2  510.77  410.96  511.77  432.85  511.95  455.48  510.68  491.55  511.19
  524.61  510.28  581.46  511.28  625.22  513.39  650.84  519.21  663.12  522.85
  670.94  525.97  709.19  533.47  759.45  540.88  793.77  545.18  870.04  552.04
#Mann= 3 , 0 , 0
       0     .08       0  346.23     .04       0  410.96     .08       0
Bank Sta=346.23,410.96
XS Rating Curve= 0
Exp/Cntr=0.3,0.1

Type RM Length L Ch R = 1 ,13719   ,763,712,586
XS GIS Cut Line= 5
    1901402.4812     940676.4563    1901829.6875     940676.4563
    1902084.8247     940723.9237    1902583.2321     940421.3191
    1902719.7008     940290.7839
#Sta/Elev= 30
       0  578.34  210.13   561.6   329.7  546.09  348.51  543.12  362.42  539.46
  369.42  539.12  378.71  536.12  394.37  535.29  402.84  536.74   423.4  535.03
  437.08  530.88  513.13  520.43  527.23  516.56  548.59  513.59  616.84  510.81
  632.82  506.14  646.88  500.22  655.54  504.03  658.89  506.95  674.88  510.94
  805.09  509.02  832.52  510.22  870.51  509.72  881.12   507.3  888.95   507.3
  904.34  509.18 1006.49  511.47 1209.36   527.9 1231.63  531.33 1458.65  555.45
#Mann= 3 , 0 , 0
       0     .08       0  616.84     .04       0  674.88     .08       0
#XS Ineff= 2 , 0
                          678.73          511.64
Permanent Ineff=
       F       F
Bank Sta=616.84,674.88
XS Rating Curve= 0
Exp/Cntr=0.3,0.1

Type RM Length L Ch R = 1 ,13007   ,838,820,784
XS GIS Cut Line= 4
 1902392.8618775  941268.4654769   1902561.70734  941000.0439696
 1902622.3190519  940757.5986645 1902851.7762262  940683.9988218
#Sta/Elev= 30
       0  584.04   81.24  571.23  121.36   560.6  190.74  544.23  221.69  535.46
   238.1  528.49  263.46  521.27  314.57  509.37  374.78  504.91  405.08  507.04
  443.27  506.84  452.22  504.61  459.61  500.25  465.55   500.4  468.33  497.62
  469.33  497.62  472.28  500.57  484.99     501  494.39  506.63   499.4   510.2
  542.45  521.52  557.83   526.7  592.65  533.35  626.61  536.29  705.76  545.59
  738.26  547.36  749.52  548.93  756.32  551.24  777.45  553.92  807.99  554.63
#Mann= 3 , 0 , 0
       0     .08       0  443.27     .04       0  494.39     .08       0
Bank Sta=443.27,494.39
XS Rating Curve= 0
Exp/Cntr=0.3,0.1

Type RM Length L Ch R = 1 ,12187   ,852,826,768
XS GIS Cut Line= 2
 1903364.4504822  941625.7392751 1903088.4027211  940692.0483708
#Sta/Elev= 30
       0  543.99   39.59  553.46   80.07  558.56  133.82  562.56  185.76  560.69
  212.95   557.1  227.94  552.79  244.48  546.56  306.86  519.34  332.04  509.14
  347.71  503.83  353.54  499.13  357.43  497.24  374.48  498.93  378.82  494.59
  379.82  494.59  385.34  500.11  410.93  504.43   424.3  502.77  472.96  504.79
  538.49  510.47  554.37  512.94  698.34  527.35  767.07  533.07  798.86  533.57
  813.11  536.08  853.28  538.12  874.86  540.39  918.19  542.29  973.64   548.1
#Mann= 3 , 0 , 0
       0     .08       0  347.71     .04       0  410.93     .08       0
Bank Sta=347.71,410.93
XS Rating Curve= 0
Exp/Cntr=0.3,0.1

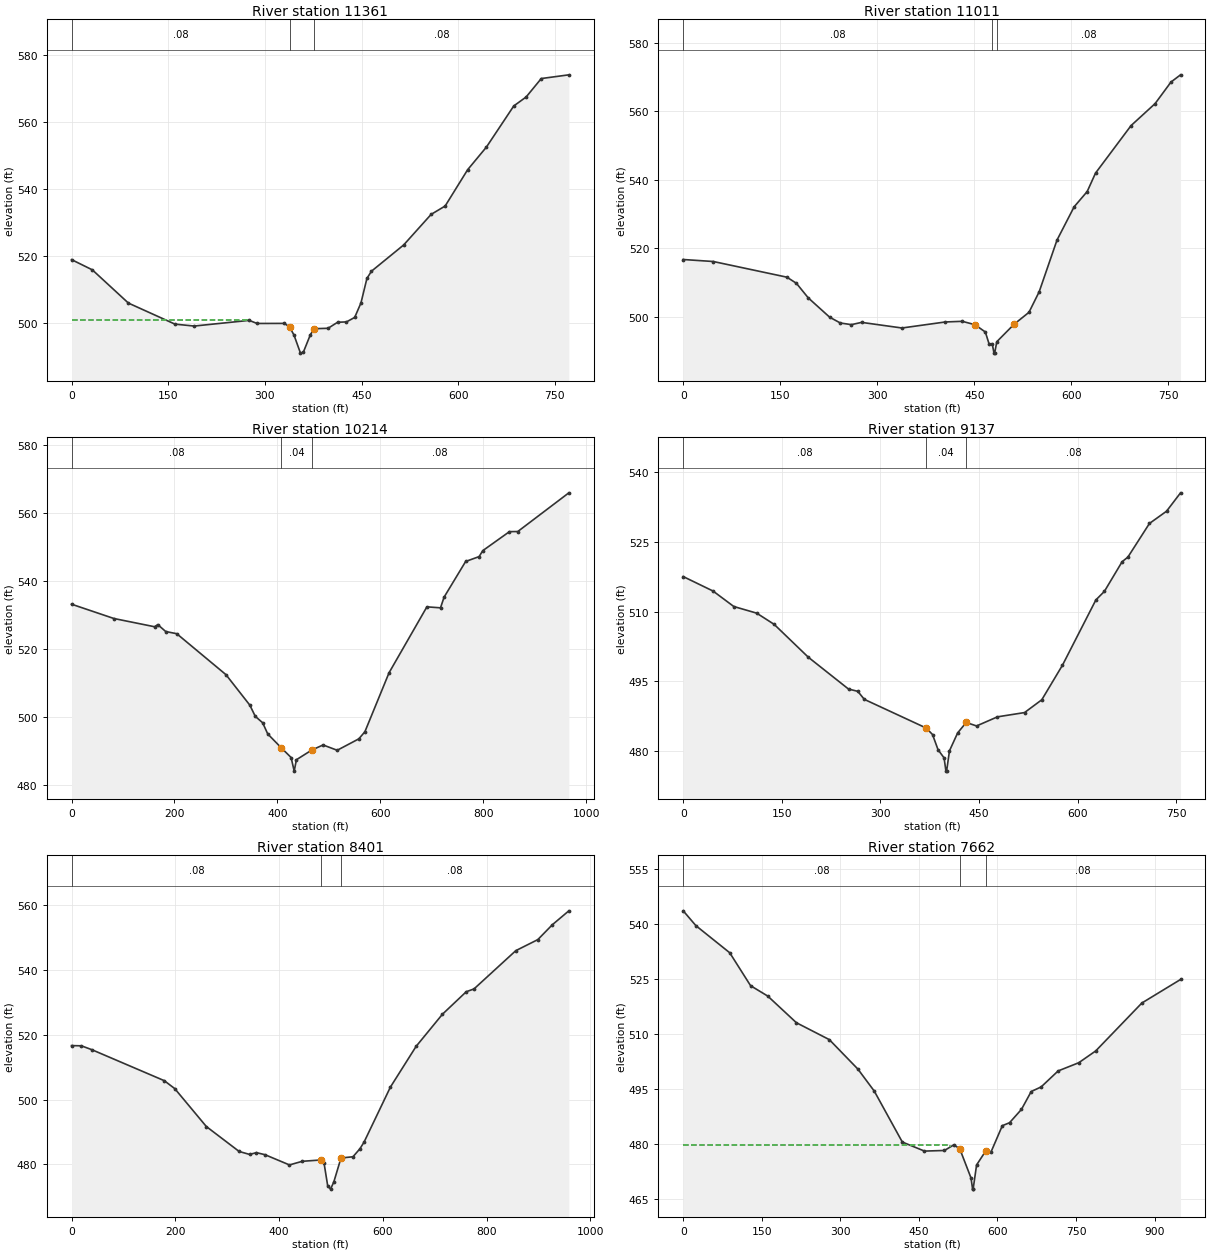
Type RM Length L Ch R = 1 ,11361   ,264,350,410
XS GIS Cut Line= 5
    1903796.0236     940914.3865    1903753.3029     940700.7833
    1903729.5692     940629.5822    1903582.4204      940544.141
    1903273.8824     940548.8877
#Sta/Elev= 30
       0  519.02   32.23  515.97   88.24  506.05  160.49  499.77   190.3   499.2
  275.67  500.89  287.81  499.97  330.15  499.99  338.22  498.94  345.17   496.5
  355.22  491.12  359.65  491.39  370.64  496.65   376.6  498.41  397.98  498.53
  412.83  500.33  426.61  500.44  439.34  501.77  449.08  506.11  458.33  513.42
  465.38  515.56  515.31  523.39  557.91  532.51  579.68  535.01  614.59  545.84
  643.78  552.61  686.14  564.86  705.35  567.54  728.81  573.04  771.62  574.15
#Mann= 3 , 0 , 0
       0     .08       0  338.22     .04       0   376.6     .08       0
#XS Ineff= 2 , 0
          275.67   500.9
Permanent Ineff=
       F       F
Bank Sta=338.22,376.6
XS Rating Curve= 0
Exp/Cntr=0.3,0.1

Type RM Length L Ch R = 1 ,11011   ,748,797,832
XS GIS Cut Line= 6
  1903869.182689  940883.1509708 1903973.0876163  940696.9869526
 1903960.0994856  940653.6921353 1903960.0994856  940541.1279004
 1903994.7349953  940354.9655433 1904137.6041962  940203.4370348
#Sta/Elev= 30
       0  516.73   46.45  516.15   160.3  511.57  174.98  509.78  193.24  505.53
  226.32  499.89  242.84  498.19  259.97  497.71  275.69  498.37  338.11  496.73
  405.05  498.49  431.31  498.68  450.97  497.69  467.04  495.55  472.79  492.06
  477.63  492.14  480.38  489.39  481.38  489.39  484.71  492.72  511.22  497.79
  534.44  501.31  550.26  507.33  577.79  522.42  604.31  532.14  624.43  536.58
  637.32  541.97  692.27  555.85  729.37  562.26     754  568.57  768.74  570.67
#Mann= 3 ,-1 , 0
       0     .08       0  477.63     .04       0  484.71     .08       0
Bank Sta=450.97,511.22
XS Rating Curve= 0
Exp/Cntr=0.3,0.1

Type RM Length L Ch R = 1 ,10214   ,1139,1077,987
XS GIS Cut Line= 4
    1904076.0811     941265.6451    1904365.6321     941151.7234
     1904583.982     940952.3604    1904849.7993     940710.2768
#Sta/Elev= 30
       0  533.14   82.36  528.93  161.32  526.51  167.56  527.14  182.95  525.11
  204.47  524.46  300.08  512.42   346.5  503.45  357.02  500.17  371.36  498.28
  381.27  494.99  407.97  490.85  426.66  488.06  432.68  484.06  436.97  487.41
   466.7  490.25  488.83  491.75  516.24  490.19  558.17  493.54  570.01  495.63
  616.98  512.98  690.51  532.36  716.98  532.07  723.91  535.21  765.82   545.7
  791.96  547.13  799.19  548.89  850.96  554.47  867.09   554.5  966.36  565.88
#Mann= 3 , 0 , 0
       0     .08       0  407.97     .04       0   466.7     .08       0
Bank Sta=407.97,466.7
XS Rating Curve= 0
Exp/Cntr=0.3,0.1

Type RM Length L Ch R = 1 ,9137    ,669,736,806
XS GIS Cut Line= 4
 1905289.9429128  941547.7115339 1905440.0284802  941293.7210391
 1905336.1219511  940964.6878199 1905353.4405068  940849.2361011
#Sta/Elev= 30
       0  517.55   45.37  514.44   76.96  511.11  111.81  509.68  138.39  507.27
  190.42  500.19  251.52  493.35  265.65  492.86  275.61  491.13  369.93  484.95
  379.39  483.56  387.83  480.28  396.95  478.54   399.8  475.69   400.8  475.69
  405.18  480.07  417.65  483.92  430.66  486.16   446.4  485.41  478.21  487.37
  519.44  488.29  545.64  491.04  577.15  498.49  627.94  512.52  640.95  514.37
   667.9  520.75  676.68  521.74  709.49  528.98  735.47  531.61  756.81  535.57
#Mann= 3 , 0 , 0
       0     .08       0  369.93     .04       0  430.66     .08       0
Bank Sta=369.93,430.66
XS Rating Curve= 0
Exp/Cntr=0.3,0.1

Type RM Length L Ch R = 1 ,8401    ,632,739,832
XS GIS Cut Line= 6
    1905528.5828     941583.6765     1905813.387     941469.7548
    1905946.2957     941408.0472    1906022.2435     941341.5929
    1906003.2565     941080.5223    1905998.5098     940938.1202
#Sta/Elev= 30
       0  516.69   19.01  516.62   39.35  515.41  178.69  505.85  198.94  503.39
  259.81  491.67  323.05  483.96  343.11  483.05  356.44   483.6  373.07  482.95
  419.97   479.8  444.68  480.92  481.06  481.34  486.77  480.26  493.66  473.36
  499.18  472.32  505.51  474.56  519.32  481.95  542.32  482.32  555.65  484.77
  563.61  486.81  614.52  503.86  663.98  516.43  714.84  526.39  760.69  533.34
  775.67  534.21   856.2  546.04  898.61  549.45  926.74  554.07  958.44  558.35
#Mann= 3 , 0 , 0
       0     .08       0  481.06     .04       0  519.32     .08       0
Bank Sta=481.06,519.32
XS Rating Curve= 0
Exp/Cntr=0.3,0.1

Type RM Length L Ch R = 1 ,7662    ,894,806,644
XS GIS Cut Line= 6
 1905341.8953765  941847.8810076 1905601.6575762  941767.0664596
 1905728.6544847   941894.061707 1905844.1045425  942015.2851901
 1905896.0570061  942015.2851901 1906167.3643362  942078.7827842
#Sta/Elev= 30
       0  543.65   24.26   539.6   88.79  532.22  128.62  523.24  161.37  520.41
  216.11  513.14  278.99  508.53  333.53   500.5  364.84  494.49  418.35  480.61
  460.68  478.14  498.79  478.31  517.01  479.86  528.22   478.7  549.54  470.81
  552.58  467.77  553.58  467.77  560.17  474.36  577.94  478.25  587.85  477.94
  609.33  485.07  623.09  485.87   645.9  489.52  664.47  494.38  683.47  495.64
  715.92     500  755.22  502.23  787.65  505.45  875.83  518.52  949.64  524.93
#Mann= 3 , 0 , 0
       0     .08       0  528.22     .04       0  577.94     .08       0
#XS Ineff= 2 , 0
           509.3  479.85
Permanent Ineff=
       F       F
Bank Sta=528.22,577.94
XS Rating Curve= 0
Exp/Cntr=0.3,0.1

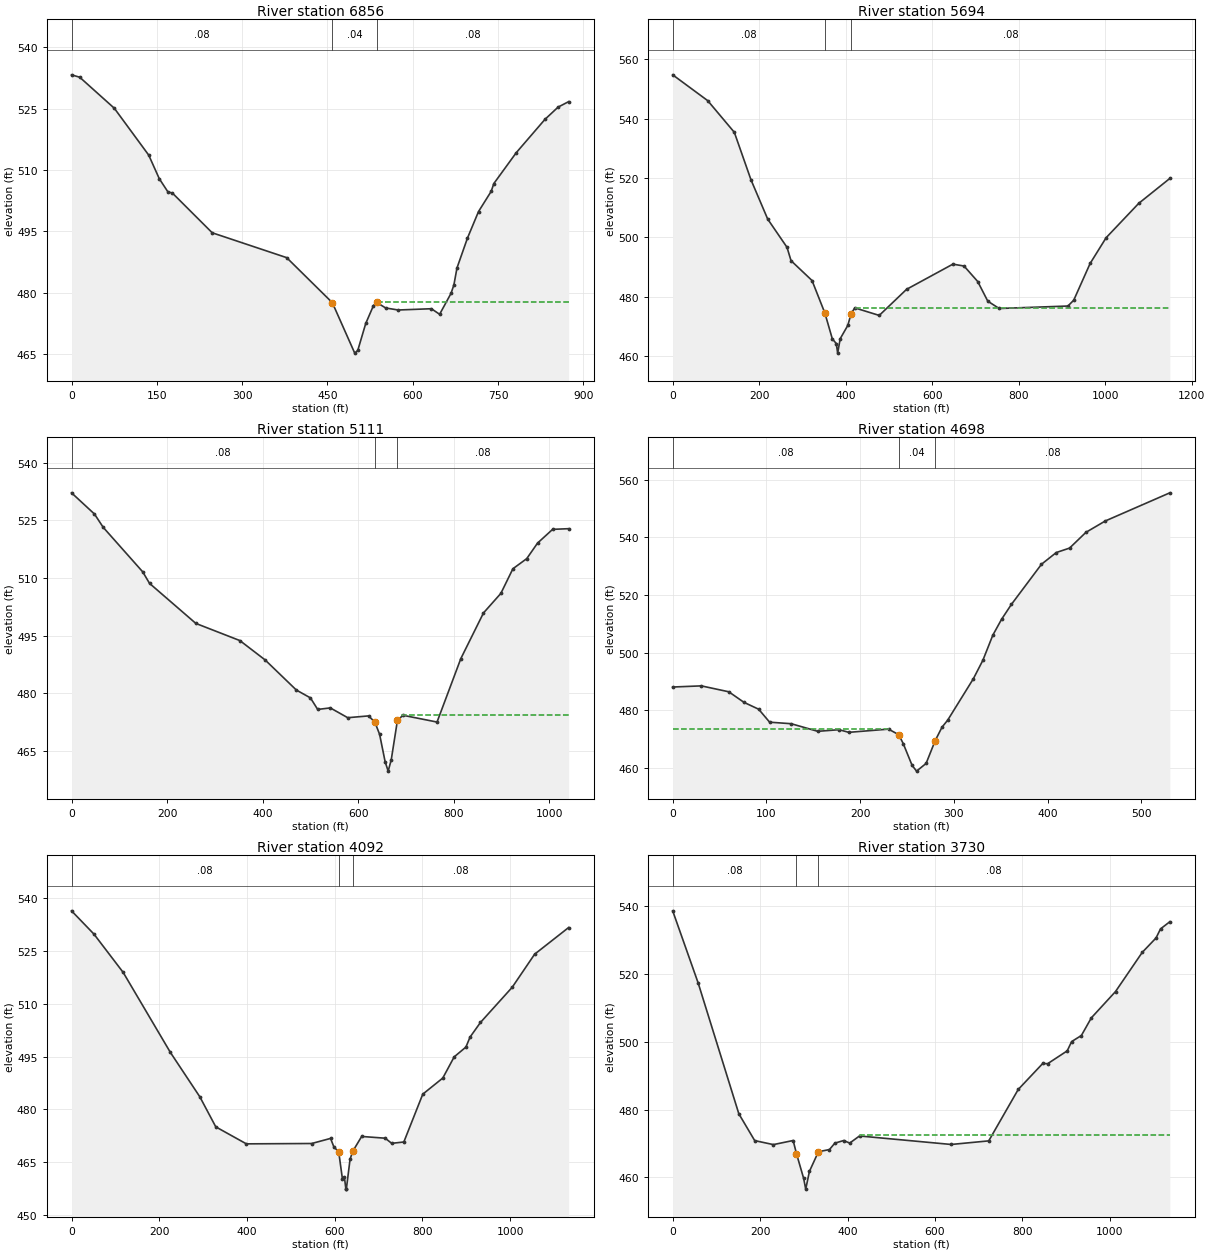
Type RM Length L Ch R = 1 ,6856    ,1200,1162,1150
XS GIS Cut Line= 6
    1905490.6089     942524.4799    1905784.9066      942467.519
    1905894.0815     942439.0386    1905998.5098     942329.8637
    1906026.9902     942230.1821    1906202.6195     942121.0072
#Sta/Elev= 30
       0  533.26   14.42  532.67   75.25  525.09  135.78  513.63  154.29  507.88
  169.41  504.67   177.5  504.35  247.37  494.66  378.34  488.58   458.6  477.58
  497.98  465.25  503.31  465.91  517.33   472.5  530.89  476.86  536.72  477.63
  552.43  476.28  574.52  475.79   632.8   476.1  647.24  474.74  667.34  479.87
  672.36  481.94  677.79  486.07  696.17  493.35  715.66  499.85  737.89  504.78
  742.61   506.7  782.03  514.24  832.42  522.37  855.56  525.37  874.13  526.71
#Mann= 3 , 0 , 0
       0     .08       0   458.6     .04       0  536.72     .08       0
#XS Ineff= 2 , 0
                          536.78          477.63
Permanent Ineff=
       F       F
Bank Sta=458.6,536.72
XS Rating Curve= 0
Exp/Cntr=0.3,0.1

Type RM Length L Ch R = 1 ,5694    ,585,583,540
XS GIS Cut Line= 5
 1906334.7685188  943319.8730552  1906196.228141  942811.8921249
 1906184.6829513  942482.8588464 1906213.5450356  942361.6353633
 1906190.4547156  942194.2328419
#Sta/Elev= 30
       0  554.71   80.95  546.03  142.54  535.37  181.05  519.39  219.75  506.17
  264.31   496.7  273.61  492.21  322.15  485.53  351.65  474.66  351.91  474.56
  369.07  465.91  378.22  464.33  381.44  461.11   387.3  465.97  404.88  470.43
  412.62  474.43  421.08  476.33  477.54  473.79  540.68  482.56  647.88  491.04
  673.62   490.4   705.2   485.2  728.56  478.57  754.89  476.12  913.77  476.95
  927.24  478.92  965.09  491.26 1002.12  499.93 1077.54  511.49 1149.37  519.86
#Mann= 3 ,-1 , 0
       0     .08       0  351.91     .04       0  412.62     .08       0
#XS Ineff= 2 , 0
                             421          476.42
Permanent Ineff=
       F       F
Bank Sta=351.65,412.62
XS Rating Curve= 0
Exp/Cntr=0.3,0.1

Type RM Length L Ch R = 1 ,5111    ,374,413,473
XS GIS Cut Line= 6
    1906425.7162     943084.5949    1906492.1705     942918.4591
    1906644.0661     942804.5374    1906639.3194     942657.3886
    1906487.4238     942401.0647    1906520.6509      942177.968
#Sta/Elev= 30
       0  532.15   48.02  526.63   66.36  523.16   148.9   511.6  163.24  508.59
  260.13  498.17  352.21  493.71  404.96  488.68  470.36  480.84  499.82   478.8
  515.05  475.79  541.41  476.19  577.89  473.64  621.46  474.11  634.71  472.48
   644.6   469.3  656.11  462.19  662.51  459.74  668.91  462.68  681.89  472.96
  693.52  474.27  764.72  472.51  814.54  489.03  861.91   500.9  898.23  505.98
  923.48   512.4  952.36  515.02     975  519.07 1006.58  522.65  1040.1  522.82
#Mann= 3 , 0 , 0
       0     .08       0  634.71     .04       0  681.89     .08       0
#XS Ineff= 2 , 0
                          692.38          474.29
Permanent Ineff=
       F       F
Bank Sta=634.71,681.89
XS Rating Curve= 0
Exp/Cntr=0.3,0.1

Type RM Length L Ch R = 1 ,4698    ,575,606,653
XS GIS Cut Line= 3
 1906773.4154247  942628.7774336 1906969.0741281  942364.3737595
 1907016.6668001  942168.7150562
#Sta/Elev= 30
       0  488.1130.50998  488.5159.83997  486.4676.01999   482.891.73999  480.41
  103.41  475.92  126.36  475.39  154.77  472.75  177.43  473.31   187.9   472.4
  230.24  473.51  241.13  471.58  245.92   468.5  255.38  460.95  260.13  458.95
   270.3  461.61     280  469.51  287.29  474.19  293.35  476.63  320.72  490.98
   330.9   497.4   341.5   506.1  350.79  511.58  361.25  516.73  393.38  530.67
  409.19  534.74  423.34  536.28  440.76  541.73  461.45  545.68  530.29  555.44
#Mann= 3 , 0 , 0
       0     .08       0  241.13     .04       0     280     .08       0
#XS Ineff= 2 , 0
          230.29  473.67
Permanent Ineff=
       F       F
Bank Sta=241.13,280
XS Rating Curve= 0
Exp/Cntr=0.3,0.1

Type RM Length L Ch R = 1 ,4092    ,366,362,327
XS GIS Cut Line= 6
 1906565.6686342   943158.242298 1906825.4308932  942915.7969929
 1907056.3326698  942956.2042669 1907206.4182372  942956.2042669
 1907316.0948695  942921.5704184 1907443.0901169  942673.3516878
#Sta/Elev= 30
       0  536.49   51.24  529.85  117.77  518.96  225.52  496.16  292.67  483.52
  328.98  474.98   398.7  470.14  547.72  470.24  590.72  471.69  598.64  469.15
  609.18  467.96  617.93     460  622.15  460.78  625.68  457.25  626.68  457.25
   635.2  465.77  641.31  468.02  661.63  472.25  715.26  471.75   730.1  470.29
  757.81  470.67  800.99  484.29  846.65  488.88  872.63  494.91   899.4   497.7
  908.79  500.54  932.52   504.7 1004.85  514.71 1056.07  524.14 1133.66  531.74
#Mann= 3 , 0 , 0
       0     .08       0  609.18     .04       0  641.31     .08       0
#XS Ineff= 2 , 0
          591.13   471.5
Permanent Ineff=
       F       F
Bank Sta=609.18,641.31
XS Rating Curve= 0
Exp/Cntr=0.3,0.1

Type RM Length L Ch R = 1 ,3730    ,336,314,259
XS GIS Cut Line= 6
    1906639.3194     943288.7047      1906900.39     943255.4775
    1907047.5388     943222.2503    1907194.6877      943136.809
    1907403.5441     942951.6863    1907531.7061     942709.6027
#Sta/Elev= 30
       0   538.7   58.38  517.35  151.31  478.76  187.61  470.84  230.37  469.66
  275.56  470.87  283.09  467.02  299.58  459.68  304.31  456.51  312.81  461.76
  333.34  467.55  358.63   468.2  370.95  470.09  391.33  470.87  404.87   470.1
  427.37  472.21  637.09   469.7  722.96  470.76  790.39  485.94  846.58  493.63
  857.69  493.55  902.52  497.35  912.56  500.08  934.89  501.88  957.65  507.09
 1012.96  514.86  1074.1  526.43 1105.63  530.68 1115.89  533.36 1137.19  535.48
#Mann= 3 , 0 , 0
       0     .08       0  283.09     .04       0  333.34     .08       0
#XS Ineff= 2 , 0
                          429.37          472.43
Permanent Ineff=
       F       F
Bank Sta=283.09,333.34
XS Rating Curve= 0
Exp/Cntr=0.3,0.1

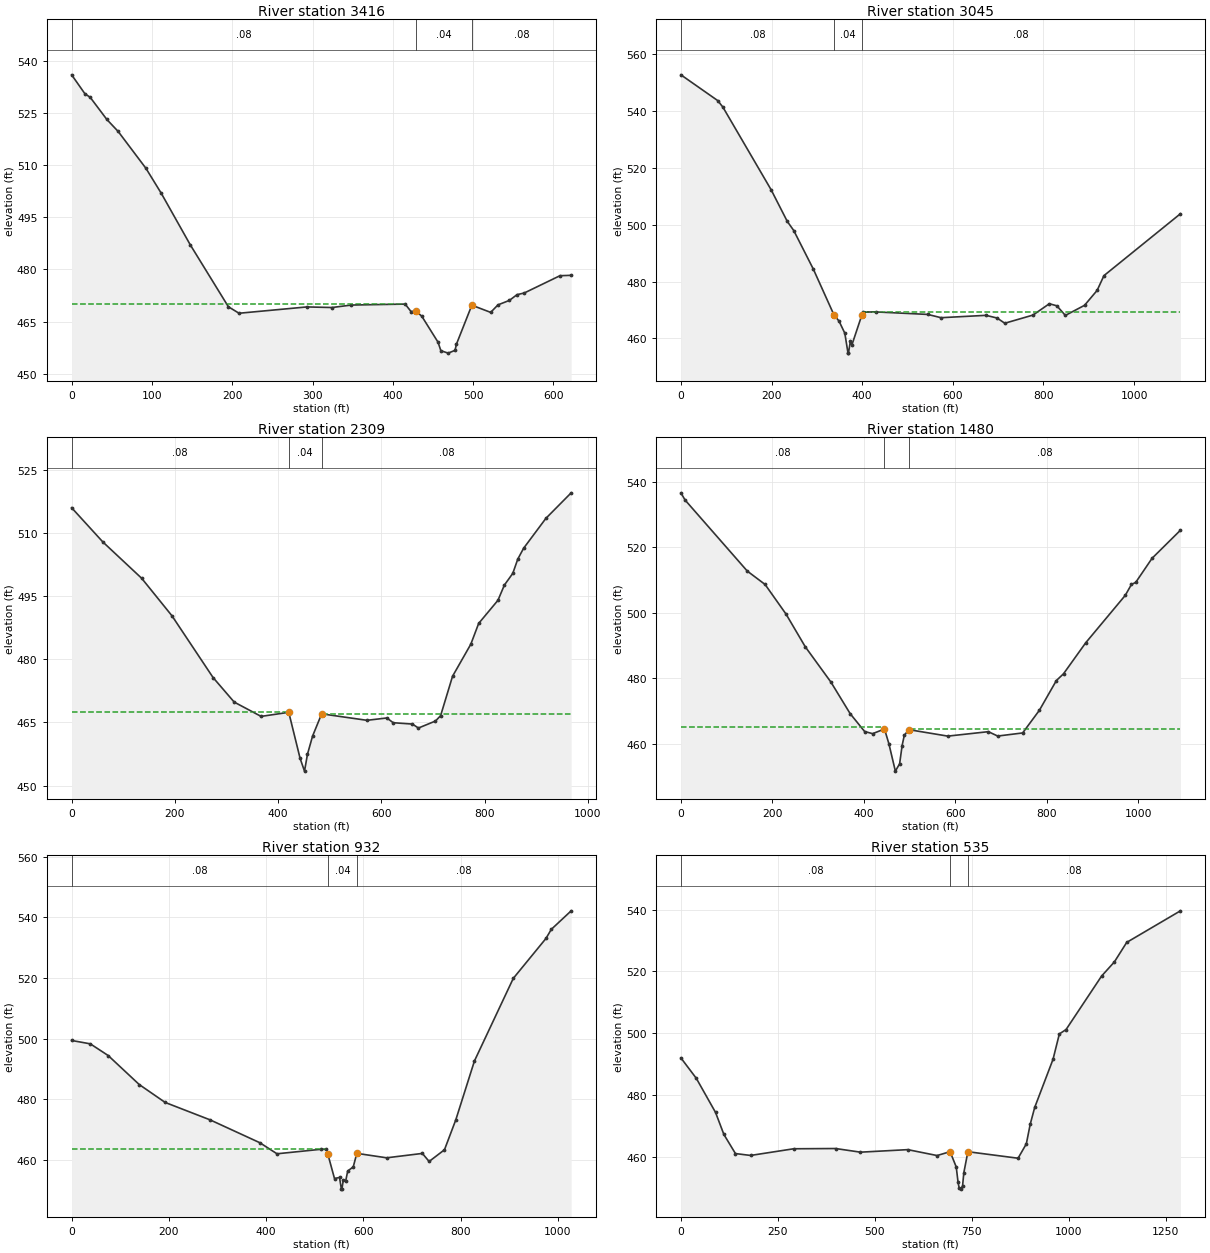
Type RM Length L Ch R = 1 ,3416    ,362,371,386
XS GIS Cut Line= 3
 1907090.6997861  943792.1535043 1907159.4447568  943400.8360976
 1907307.5107881  943231.6177676
#Sta/Elev= 30
       0  536.0316.42999  530.6123.10999  529.5543.87994  523.1757.96997  519.72
92.56995   509.1  111.69   501.9  147.67  487.12  195.22  469.26  208.47  467.39
  292.91  469.21  324.22  469.04  348.27  469.75   415.4  470.03  422.79  467.85
   428.6  468.06  436.05  466.55  456.31  459.07  459.87  456.61  468.94  455.91
  477.49  456.71  479.33  458.53  498.44  469.71  521.88  467.64  530.98   469.8
  545.18  471.09  554.72  472.74  563.68  473.22  608.22   478.2  622.16  478.31
#Mann= 3 , 0 , 0
       0     .08       0   428.6     .04       0  498.44     .08       0
#XS Ineff= 2 , 0
          415.58  470.02  498.44          469.71
Permanent Ineff=
       F       F
Bank Sta=428.6,498.44
XS Rating Curve= 0
Exp/Cntr=0.3,0.1

Type RM Length L Ch R = 1 ,3045    ,788,736,650
XS GIS Cut Line= 4
 1907064.2982123  943869.0305472 1907397.1798281  943666.0552154
 1907502.7275677  943584.8644183  1907803.132212    943089.60281
#Sta/Elev= 30
       0  552.71   81.32  543.64    92.7  541.34  199.08  512.29   234.7  501.17
  248.99  497.96  292.25  484.37  337.63  468.32  348.93   466.1  361.74  461.83
  368.73  454.84  369.73  454.84  373.96  459.07  377.04   457.6  399.24  468.21
  402.34  469.28  430.56  469.33  544.74  468.45  574.11   467.3  673.15  468.13
   697.6  467.19  714.72  465.35  777.02  468.23  812.98  472.21  829.55  471.48
  848.38   468.1  890.63  471.65  918.49  476.91  933.49  482.09 1102.29  503.86
#Mann= 3 , 0 , 0
       0     .08       0  337.63     .04       0  399.24     .08       0
#XS Ineff= 2 , 0
                          402.67           469.4
Permanent Ineff=
       F       F
Bank Sta=337.63,399.24
XS Rating Curve= 0
Exp/Cntr=0.3,0.1

Type RM Length L Ch R = 1 ,2309    ,824,829,868
XS GIS Cut Line= 5
    1907958.9124     944090.9033    1908058.5939     943801.3523
    1908082.3276     943421.6133    1908072.8341     943350.4122
    1908148.7819      943155.796
#Sta/Elev= 30
       0  515.97   60.42  507.85  135.59  499.23  194.24  490.33  273.87  475.67
  314.79  469.84  366.96  466.44  420.49  467.41  442.47  456.47  450.99  453.45
  456.77  457.48  466.59  461.76  484.24  467.05  572.04  465.51  610.47  466.07
  622.74  464.94  659.99  464.62  671.61  463.68  704.61  465.34  714.56  466.61
   737.7  475.97  773.09  483.58  788.29  488.51   825.7  494.01  838.07  497.61
  854.36  500.39  864.05  503.78  875.32  506.35  918.48  513.45  967.45  519.51
#Mann= 3 , 0 , 0
       0     .08       0  420.49     .04       0  484.24     .08       0
#XS Ineff= 2 , 0
          419.95  467.49  484.75           467.1
Permanent Ineff=
       F       F
Bank Sta=420.49,484.24
XS Rating Curve= 0
Exp/Cntr=0.3,0.1

Type RM Length L Ch R = 1 ,1480    ,536,548,532
XS GIS Cut Line= 6
     1908329.158     944271.2793    1908651.9361     944152.6109
    1908732.6306     944105.1435     1908780.098     944010.2088
    1908860.7926     943867.8066    1909183.5707     943658.9501
#Sta/Elev= 30
       0  536.68    9.09  534.48  145.12  512.78  183.97   508.7  229.69  499.67
  271.72  489.69  327.95  478.87  369.98  469.24  401.53   463.8  419.04  463.14
  444.91  464.57  454.55  460.08  468.71   451.7  478.05  453.95  483.47   459.5
  488.25  462.63     498  464.37  583.34  462.39  672.03  463.75   692.3  462.41
  746.95  463.36  783.48  470.28  820.63  479.36  836.27  481.43  884.86  490.91
  971.14  505.36  984.66  508.69  994.14  509.35 1029.83   516.7 1091.79  525.26
#Mann= 3 , 0 , 0
       0     .08       0  444.91     .04       0     498     .08       0
#XS Ineff= 2 , 0
          444.07  465.08  503.52          464.64
Permanent Ineff=
       F       F
Bank Sta=444.91,498
XS Rating Curve= 0
Exp/Cntr=0.3,0.1

Type RM Length L Ch R = 1 ,932     ,392,397,413
XS GIS Cut Line= 6
  1908793.858622  944485.9221443 1909036.3055883  944306.9728314
   1909192.16292  944255.0203677 1909238.3436194  944185.7510094
 1909284.5226577  943949.0774685 1909359.5654414  943723.9490581
#Sta/Elev= 30
       0  499.43   38.38  498.32   75.08  494.47  139.06  484.89  192.38  478.99
  284.78  473.24  387.08   465.7   422.4  462.05  512.72  463.53  524.12  463.51
     527  461.93   540.7  453.88     551  454.24  554.85  450.39  555.85  450.39
  558.76   453.3  563.78  453.15   567.9  456.37  579.29  457.73  586.57  462.19
  647.98  460.72  721.45  462.17  735.33  459.51  766.93  463.38  790.24  473.26
  828.58  492.68  908.47  519.92  975.69  533.09  986.67  536.09 1027.54   542.2
#Mann= 3 , 0 , 0
       0     .08       0     527     .04       0  586.57     .08       0
#XS Ineff= 2 , 0
          524.09  463.58
Permanent Ineff=
       F       F
Bank Sta=527,586.57
XS Rating Curve= 0
Exp/Cntr=0.3,0.1

Type RM Length L Ch R = 1 ,535     ,535,535,535
XS GIS Cut Line= 6
 1908884.1302421  944488.6216816 1909408.1621564  944515.7735586
  1909473.326768  944515.7735586 1909571.0736557  944382.7291952
 1909687.8268811  944195.3810184 1909606.3711314  943893.9948159
#Sta/Elev= 30
       0  492.01   39.67  485.41   89.29  474.37  110.83  467.23   140.6  461.05
  179.67  460.44  290.72   462.6  398.85  462.68     463   461.5  584.94  462.32
  660.49  460.41  694.08  461.66  709.94   456.7  714.65   451.7  717.28  450.05
  722.17  449.54   726.3  450.69  729.53  454.88  739.95  461.65  869.35  459.54
  890.65   464.2  900.61  470.52  912.25  475.99  959.53  491.58  975.78  499.77
  993.09  501.19 1084.81  518.52 1117.68  523.08 1149.44  529.39 1287.98  539.61
#Mann= 3 , 0 , 0
       0     .08       0  694.08     .04       0  739.95     .08       0
Bank Sta=694.08,739.95
XS Rating Curve= 0
Exp/Cntr=0.3,0.1

Chan Stop Cuts=-1
Chan Mod GeomFile=Modified Geometry