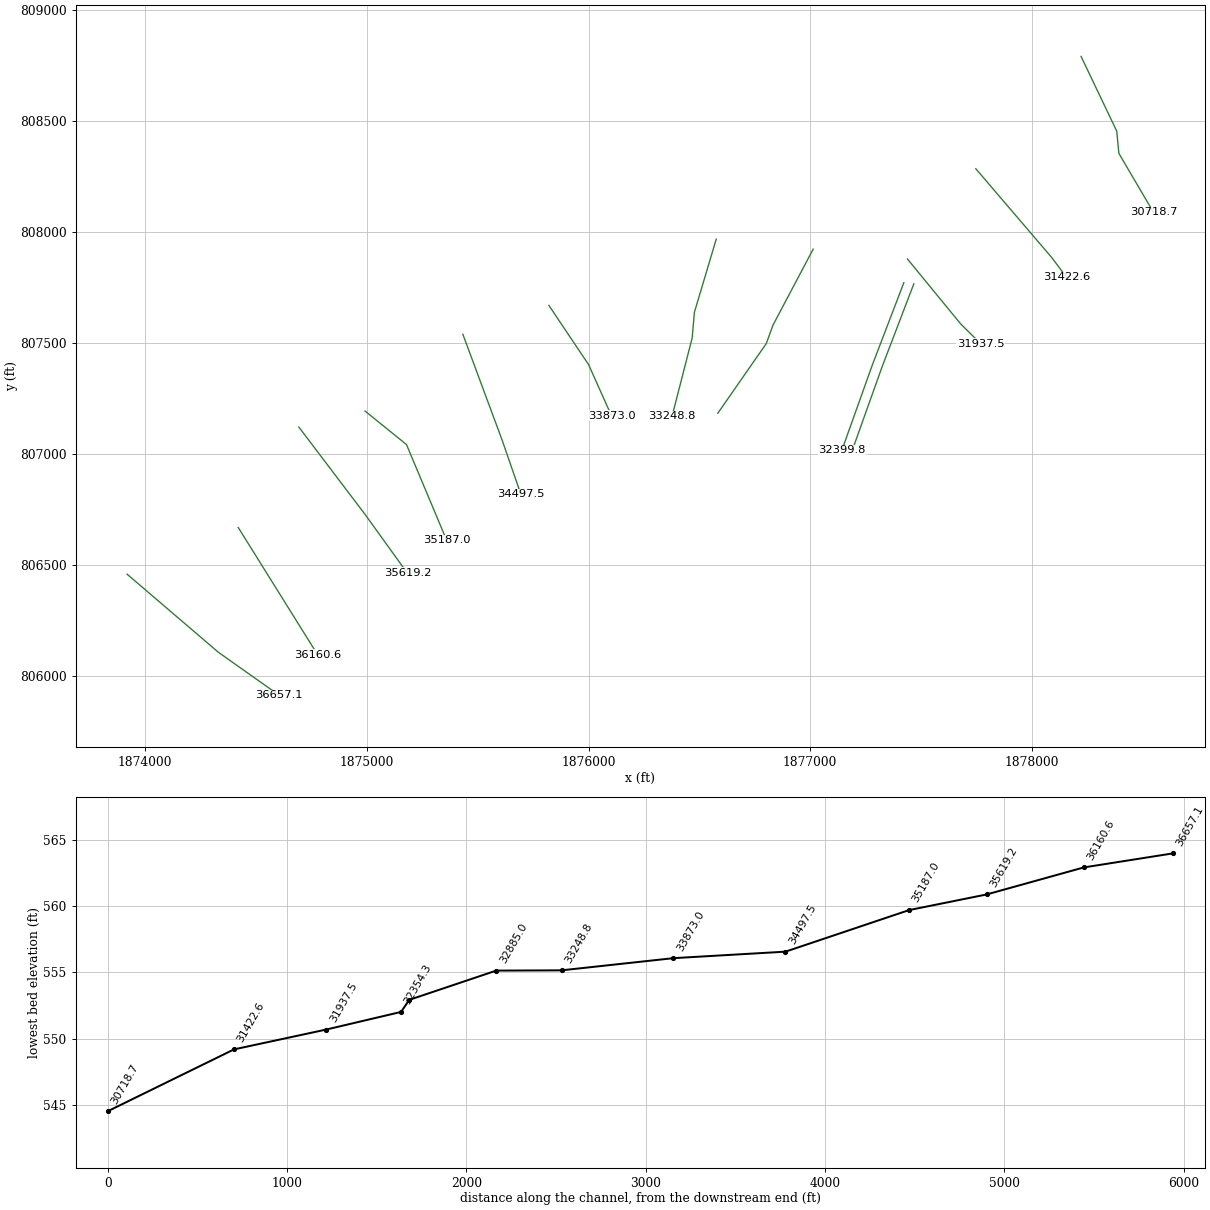
--- VARNALS CREEK.PRJ (project) ---

Proj Title=Varnals Creek
Current Plan=p01
Default Exp/Contr=0.3,0.1
English Units
Geom File=g01
Flow File=f01
Plan File=p01
Y Axis Title=Elevation
X Axis Title(PF)=Main Channel Distance
X Axis Title(XS)=Station
BEGIN DESCRIPTION:
####(Watershed Name)####
VARNALS CREEK
HCFCD Unit X###-##-##
(Flood Hazard, Floodway) Model
10, 2, 1, 0.2% Event
Filename:  n:\NC_flood\60273\Approximates\Eng\Haw-Big_Alamance\Eng\Varnals Creek\Varnals Creek.prj
Prepared by:  ________     Date: ________
Reviewed by:  ________     Date: ________
STATUS (Draft RAS, SVSQ, FINAL)
END DESCRIPTION:
DSS Export Rating Curves= 0
DSS Export Rating Curve Sorted= 0
DSS Export Volume Flow Curves= 0
DXF OffsetX= 0
DXF OffsetY= 0
DXF ScaleX= 1
DXF ScaleY= 10

--- VARNALS CREEK.p01 (plan) ---

Plan Title=100-Year-Single
Program Version=3.10
Short Identifier=Plan01
Geom File=g01
Flow File=f01
Subcritical Flow
K Sum by GR= 0
Std Step Tol= 0.01
Critical Tol= 0.01
Num of Std Step Trials= 20
Max Error Tol= 0.3
Flow Tol Ratio= 0.001
Split Flow NTrial= 30
Split Flow Tol= 0.02
Split Flow Ratio= 0.02
Log Output Level= 0
Friction Slope Method= 1
Unsteady Friction Slope Method= 2
Parabolic Critical Depth
Global Vel Dist= 0 , 0 , 0
Global Log Level= 0
CheckData=True
Encroach Param=-1 ,10,10, 2
Encroach River=Varnals Creek
Encroach Reach=Reach - 1
Encroach Node=36657.1
       1    4935  5085.5
Encroach Node=36160.6
       4      .7
Encroach Node=35619.2
       4      .7
Encroach Node=35187.0
       4      .7
Encroach Node=34497.5
       4      .7
Encroach Node=33873.0
       4      .7
Encroach Node=33248.8
       1    4860    5043
Encroach Node=32885.0
       1  4946.5    5088
Encroach Node=32399.8
       1    4963    5035
Encroach Node=32377.0
       1    4963    5035
Encroach Node=32354.3
       1    4963    5035
Encroach Node=31937.5
       1    4978  5022.5
Encroach Node=31422.6
       4      .7
Encroach Node=30718.7
       1  4975.5  5036.5
Computation Interval=1HOUR
Output Interval=1HOUR
Run HTab= 0
Run UNet= 0
Run PostProcess= 0
UNET Theta= 1
UNET Theta Warmup= 1
UNET ZTol= 0.02
UNET ZSATol= 0.05
UNET MxIter= 20
UNET MaxInSteps= 1
UNET DtIC= 0
UNET DtMin= 0
UNET MaxCRTS= 20
UNET WFStab= 2
UNET SFStab= 1
UNET WFX= 1
UNET SFX= 1
UNET DSS MLevel= 4
UNET Convert EG Bridges=-1
UNET Use Existing IB Tables=-1
UNET Froude Reduction=False
UNET Froude Limit= 1
UNET Froude Power= 10
Instantaneous Interval=1HOUR
Write IC File= 0
Echo Input=False
Echo Output=False
Write Detailed= 0

--- VARNALS CREEK.f01 (steady flow) ---

Flow Title= 100-Year-Single
Program Version=3.10
Number of Profiles= 2
Profile Names=100-Year,AFW
River Rch & RM=Varnals Creek,Reach - 1       ,36657.1
    1370    1370
River Rch & RM=Varnals Creek,Reach - 1       ,33248.8
    1550    1550
River Rch & RM=Varnals Creek,Reach - 1       ,32399.8
    1890    1890
River Rch & RM=Varnals Creek,Reach - 1       ,30718.7
    1890    1890
Boundary for River Rch & Prof#=Varnals Creek,Reach - 1       , 1
Up Type= 0
Dn Type= 1
Dn Known WS=554.2
Boundary for River Rch & Prof#=Varnals Creek,Reach - 1       , 2
Up Type= 0
Dn Type= 1
Dn Known WS=554.9
DSS Import GetInterval= 0
DSS Import GetPeak= 0
DSS Import FillOption= 0

--- VARNALS CREEK.g01 (geometry) ---

Geom Title=Geom 01 by CodeH2 for Windows

River Reach=Varnals Creek,Reach - 1
Reach XY= 312
      1874330.37       806105.67       1874330.5       806109.69
         1874333       806114.69         1874338       806124.75
      1874343.12       806132.31      1874345.63       806139.88
      1874345.63       806149.94      1874343.12       806159.94
      1874333.37          806164       1874327.5       806168.19
      1874320.75       806170.31       1874316.5        806174.5
         1874310       806179.37         1874310       806191.94
         1874310        806199.5       1874317.5       806209.56
      1874327.62       806214.56      1874377.87       806212.06
         1874403       806232.19         1874413       806257.31
      1874433.13          806285      1874440.62          806290
      1874466.88       806301.25      1874480.88       806307.63
      1874495.88       806317.63         1874511       806335.25
       1874518.5       806357.88      1874526.12       806365.44
      1874557.37       806365.94      1874575.25       806365.94
      1874605.62       806364.56      1874631.75       806381.06
      1874649.75       806389.37      1874664.88       806403.13
         1874669       806416.94         1874669       806430.69
      1874688.25       806452.75      1874715.88       806473.44
      1874724.63       806488.63      1874744.75       806498.69
      1874754.75       806503.69      1874769.87       806511.25
      1874779.88       806518.75      1874789.87       806528.81
         1874800       806536.38       1874812.5       806546.44
      1874825.12          806554      1874835.12          806559
      1874850.25       806569.06      1874865.25       806584.12
      1874875.37       806591.69       1874890.5       806606.75
       1874894.5       806610.75      1874915.63       806631.87
      1874952.13       806665.06      1874959.75       806680.13
      1874966.63       806695.19      1874974.75       806707.13
      1874984.88       806716.56      1874991.75        806723.5
      1874996.75       806730.38      1875001.13       806737.31
      1875004.37       806744.81         1875005        806755.5
         1875008       806789.94      1875013.75       806815.06
      1875019.37        806841.5         1875025       806855.81
       1875032.5       806862.69       1875037.5       806867.12
      1875050.13       806879.06         1875057       806885.94
       1875069.5       806897.25       1875076.5       806901.69
      1875085.88       806903.56      1875092.75       806904.81
      1875097.87       806906.69      1875106.63       806916.12
         1875106       806928.69       1875096.5          806940
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
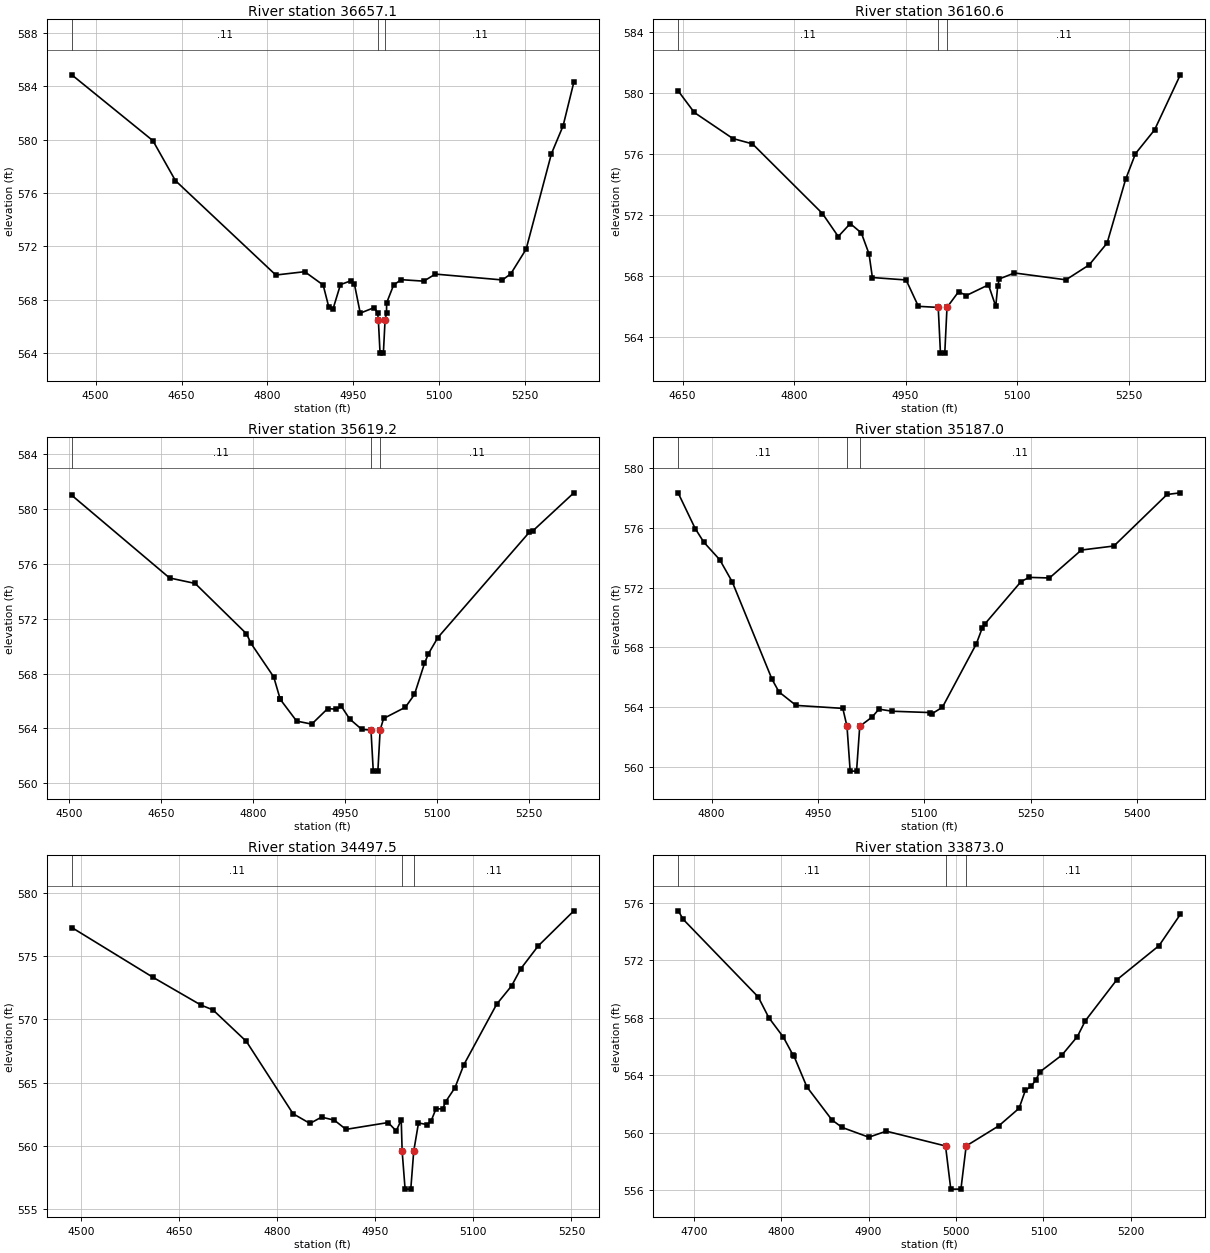
Type RM Length L Ch R = 1 ,36657.1,496.5,496.5,496.5
XS GIS Cut Line= 3
      1873918.50       806457.62      1874330.58       806105.42
      1874604.58       805911.96
BEGIN DESCRIPTION:
Varnals Creek 11.0
END DESCRIPTION:
#Sta/Elev= 30
  4458.2  584.87    4600  579.93  4639.4  576.93  4814.8  569.85  4865.3   570.1
  4897.6   569.1  4907.2  567.48    4915  567.33  4927.8  569.13  4946.1  569.42
  4952.1  569.19  4962.4  566.99    4987  567.41  4992.8  566.99    4994  566.49
    4997  563.99  5002.8  563.99  5005.8  566.49  5008.3  566.99  5008.5  567.76
  5020.8  569.11  5034.2   569.5  5073.4  569.39  5093.6  569.92  5210.9  569.48
  5225.5  569.94  5252.3  571.79  5296.5  578.95  5316.9  581.04  5335.7  584.32
#Mann= 3 , 1 , 0
 4458.20    0.11       0    4994   0.042       0  5005.8    0.11       0
Bank Sta=4994.00,5005.80
Exp/Cntr=0.3,0.1

Type RM Length L Ch R = 1 ,36160.6,541.4,541.4,541.4
XS GIS Cut Line= 2
      1874419.80       806668.02      1874777.65       806095.09
BEGIN DESCRIPTION:
Varnals Creek 10.0
END DESCRIPTION:
#Sta/Elev= 30
  4644.2  580.13  4665.8  578.72  4717.7  577.01  4744.1  576.66  4838.2  572.09
  4859.5  570.58  4875.6  571.43  4890.5  570.82  4900.9  569.44  4905.4  567.89
  4950.8  567.73  4967.3     566    4994  565.93    4997  562.93  5002.8  562.93
  5005.8  565.93  5021.4  566.96  5031.8  566.71  5061.6  567.41  5071.4     566
    5074  567.33  5076.3   567.8  5096.6  568.19  5165.8  567.74  5197.1  568.72
  5221.2  570.15  5246.1  574.33  5259.4  576.02  5285.1  577.58  5319.7  581.19
#Mann= 3 , 1 , 0
 4644.20    0.11       0    4994   0.042       0  5005.8    0.11       0
Bank Sta=4994.00,5005.80
Exp/Cntr=0.3,0.1

Type RM Length L Ch R = 1 ,35619.2,432.2,432.2,432.2
XS GIS Cut Line= 3
      1874693.28       807120.61      1874991.00       806728.28
      1875182.45       806462.69
BEGIN DESCRIPTION:
Varnals Creek 9.0
END DESCRIPTION:
#Sta/Elev= 28
  4503.9  581.01  4663.6  574.98  4705.4  574.58  4789.2  570.91  4796.7   570.2
  4833.7  567.76  4844.2  566.15  4844.3  566.13  4871.1  564.54  4895.8  564.32
  4921.8  565.45  4935.6  565.41  4944.2  565.61  4957.8  564.69  4977.6  563.93
  4992.5  563.89 4996.25  560.89 5003.75  560.89  5007.5  563.89  5013.1  564.73
  5048.7  565.55  5063.5  566.48  5079.9  568.75  5086.3  569.45  5101.7  570.63
  5251.2  578.32  5256.5   578.4  5323.8  581.19
#Mann= 3 , 1 , 0
 4503.90    0.11       0  4992.5   0.042       0  5007.5    0.11       0
Bank Sta=4992.50,5007.50
Exp/Cntr=0.3,0.1

Type RM Length L Ch R = 1 ,35187.0,689.5,689.5,689.5
XS GIS Cut Line= 3
      1874992.05       807192.71      1875178.74       807041.93
      1875360.19       806610.08
BEGIN DESCRIPTION:
Varnals Creek 8.0
END DESCRIPTION:
#Sta/Elev= 29
  4752.9  578.32  4776.8  575.95  4789.1  575.03  4811.5  573.86  4829.2  572.37
  4885.3  565.85  4895.1  565.01  4919.1  564.11  4985.1  563.91    4991  562.71
  4995.5  559.71  5004.5  559.71    5009  562.71  5026.4  563.33  5036.1  563.86
  5054.7  563.72  5108.5  563.63  5110.9  563.55  5125.7  563.99  5173.5  568.23
  5181.8  569.29  5185.5  569.56  5236.6   572.4  5248.1  572.68  5276.7  572.64
  5321.7  574.51  5367.6  574.78  5442.6  578.23  5461.3  578.34
#Mann= 3 , 1 , 0
 4752.90    0.11       0    4991   0.042       0    5009    0.11       0
Bank Sta=4991.00,5009.00
Exp/Cntr=0.3,0.1

Type RM Length L Ch R = 1 ,34497.5,624.5,624.5,624.5
XS GIS Cut Line= 3
      1875433.03       807538.86      1875609.44       807064.01
      1875695.05       806817.09
BEGIN DESCRIPTION:
Varnals Creek 7.0
END DESCRIPTION:
#Sta/Elev= 30
  4485.7  577.28  4609.5  573.35  4683.3  571.14  4701.6  570.76  4752.8  568.26
  4824.1  562.54    4850  561.77  4867.7  562.27  4887.2  562.03  4905.1   561.3
  4969.5  561.84  4981.9  561.18  4989.6  562.05    4991  559.57  4995.5  556.57
  5004.2  556.57  5008.7  559.57    5016  561.81  5028.7  561.68  5035.1  561.94
  5042.7  562.92  5053.1  562.93  5057.4  563.48  5071.8   564.6  5085.3  566.41
  5135.6  571.21  5158.4  572.66  5172.4  574.01  5198.9  575.81  5253.6   578.6
#Mann= 3 , 1 , 0
 4485.70    0.11       0    4991   0.042       0  5008.7    0.11       0
Bank Sta=4991.00,5008.70
Exp/Cntr=0.3,0.1

Type RM Length L Ch R = 1 ,33873.0,624.2,624.2,624.2
XS GIS Cut Line= 3
      1875821.31       807668.73      1876000.39       807401.95
      1876103.73       807171.14
BEGIN DESCRIPTION:
Varnals Creek 6.0
END DESCRIPTION:
#Sta/Elev= 28
  4682.3  575.43  4688.1  574.83  4773.8  569.44  4785.9     568  4802.5  566.65
  4813.4  565.42  4814.6  565.34  4829.4  563.19  4858.1  560.89  4869.7  560.37
  4900.3  559.69  4920.2  560.11    4988  559.08    4994  556.08  5005.6  556.08
  5011.6  559.08  5048.9  560.48  5072.1   561.7  5079.3  562.95  5085.8  563.22
    5091  563.65  5096.1  564.24  5121.1   565.4  5138.8  566.69  5147.8  567.78
  5183.8  570.63  5232.2  573.01  5256.5  575.18
#Mann= 3 , 1 , 0
 4682.30    0.11       0    4988   0.042       0  5011.6    0.11       0
Bank Sta=4988.00,5011.60
Exp/Cntr=0.3,0.1

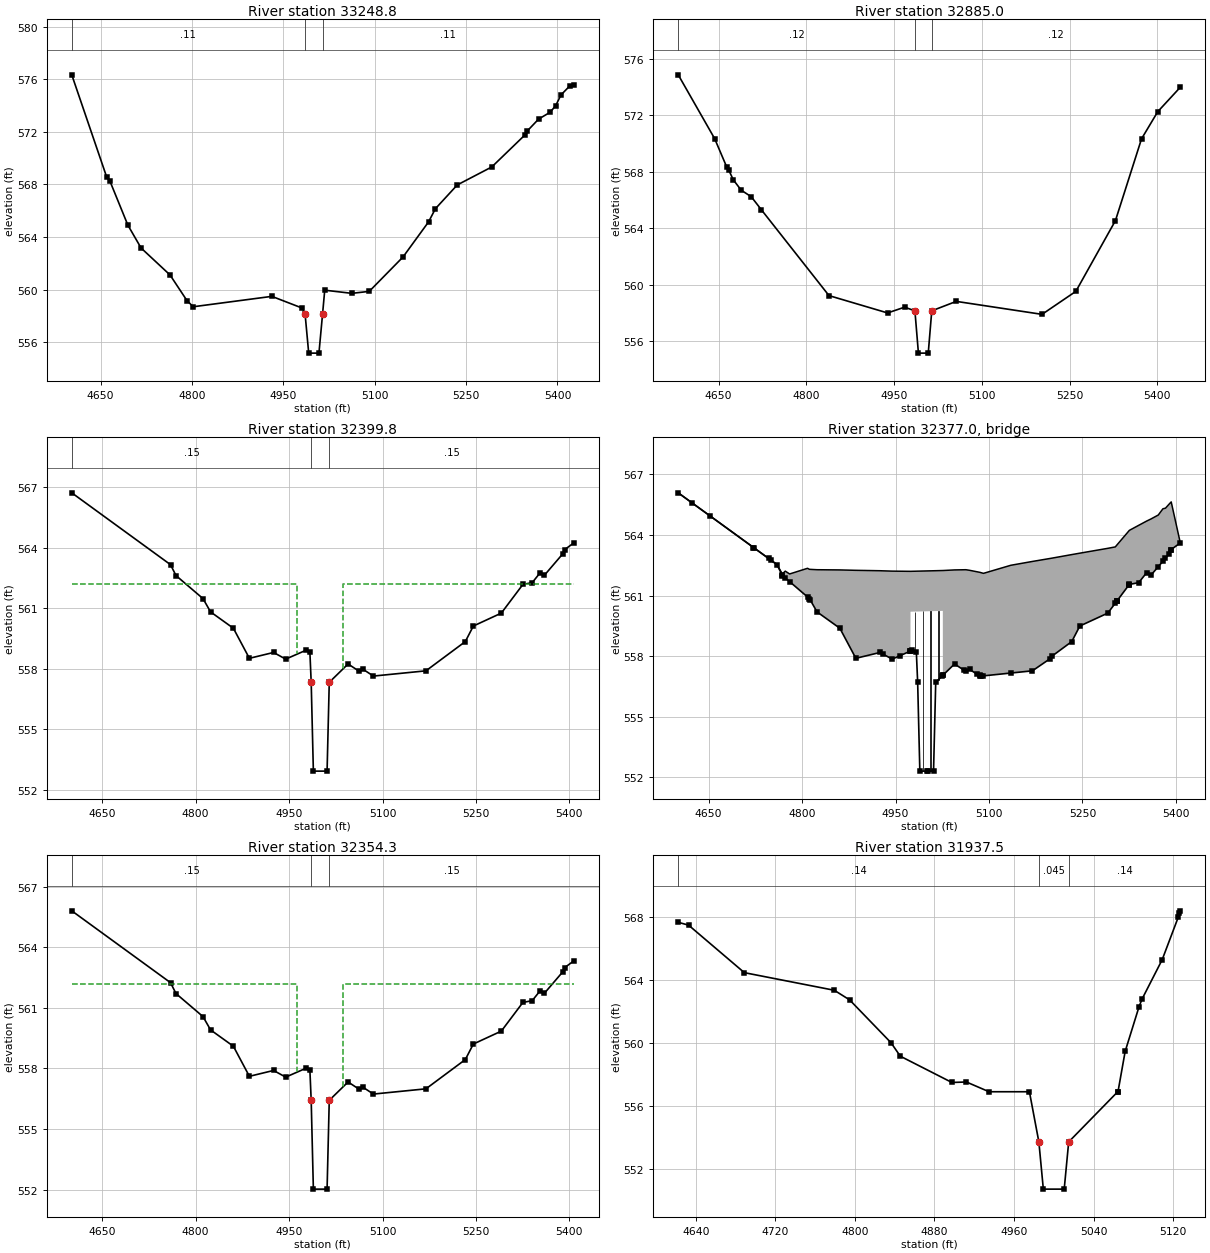
Type RM Length L Ch R = 1 ,33248.8,363.8,363.8,363.8
XS GIS Cut Line= 4
      1876575.95       807967.62      1876477.60       807638.34
      1876467.54       807522.67      1876376.82       807169.60
BEGIN DESCRIPTION:
Varnals Creek 5.0
END DESCRIPTION:
#Sta/Elev= 30
  4602.6  576.34  4659.7  568.59    4665  568.28  4694.7   564.9  4716.4  563.16
  4763.9  561.11    4792  559.14  4802.1  558.69  4931.1  559.48  4980.8  558.59
  4985.6  558.16  4991.6  555.16  5008.4  555.16  5014.4  558.16  5017.9  559.95
  5062.4  559.71    5091  559.86  5146.5  562.48  5188.4  565.15  5199.6  566.15
  5235.5  567.96  5292.2  569.33  5346.3  571.75  5350.5  572.07    5369  572.97
  5387.9  573.49  5397.2     574  5405.6   574.8  5420.3   575.5  5426.9   575.6
#Mann= 3 , 1 , 0
 4602.60    0.11       0  4985.6   0.042       0  5014.4    0.11       0
Bank Sta=4985.60,5014.40
Exp/Cntr=0.3,0.1

Type RM Length L Ch R = 1 ,32885.0,485.25,485.25,485.25
XS GIS Cut Line= 4
      1877013.24       807922.51      1876832.18       807580.50
      1876802.00       807497.52      1876583.22       807183.17
BEGIN DESCRIPTION:
Varnals Creek 4.0
END DESCRIPTION:
#Sta/Elev= 22
    4581  574.88  4643.3  570.35  4663.7  568.36  4667.1  568.15    4675  567.44
  4688.6   566.7  4705.9  566.23  4723.3   565.3  4838.7  559.22  4938.9  557.99
    4968   558.4  4985.6  558.14  4991.6  555.14  5008.4  555.14  5014.4  558.14
  5056.3  558.81  5202.9  557.89  5260.7  559.52  5328.4  564.54    5373  570.34
  5400.8  572.27  5439.3     574
#Mann= 3 , 1 , 0
 4581.00    0.12       0  4985.6   0.042       0  5014.4    0.12       0
Bank Sta=4985.60,5014.40
Exp/Cntr=0.5,0.3

Type RM Length L Ch R = 1 ,32399.8,45.5,45.5,45.5
XS GIS Cut Line= 3
      1877422.21       807771.23      1877279.41       807398.51
      1877142.53       807015.47
BEGIN DESCRIPTION:
Upstream Section of Bridge/Culvert/Weir
END DESCRIPTION:
#Sta/Elev= 30
  4601.2  566.72  4759.7  563.16  4768.5  562.62  4811.8  561.48    4824  560.82
  4860.6  560.01  4886.3  558.52  4925.1  558.81  4944.6  558.48  4976.4  558.91
  4983.4  558.83  4985.5  557.33    4989  552.93    5011  552.93  5014.5  557.33
  5044.7  558.24  5062.9  557.87    5069  557.97  5085.4  557.64  5169.7   557.9
  5232.9  559.35  5245.8  560.12  5290.7  560.76  5325.3  562.18  5340.3  562.27
    5353  562.76  5359.7  562.63  5389.4   563.7  5392.1   563.9  5407.1  564.24
#Mann= 3 , 1 , 0
 4601.20    0.15       0  4985.5    0.05       0  5014.5    0.15       0
#XS Ineff= 2 , 0
       0    4963   562.2    5036       0   562.2
Bank Sta=4985.50,5014.50
Exp/Cntr=0.5,0.3

Type RM Length L Ch R = 3 ,32377.0,,,
BEGIN DESCRIPTION:
Varnals Creek - Bass Mountain Rd
Structure ID: NCF-0130
Approximate Survey Structure
END DESCRIPTION:
Bridge Culvert--1,0,-1,-1, 0
Deck Dist Width WeirC Skew NumUp NumDn MinLoCord MaxHiCord MaxSubmerge Is_Ogee
10,25.5,2.6,, 39, 39,,,0.95,0,1,1,,
  4601.2  4759.7  4768.2    4773    4780  4808.7  4811.8    4824  4860.6  4886.3
  4925.1  4944.6 4973.91    4974 5025.89    5026  5044.7  5062.9    5069  5085.4
  5091.1    5135  5169.7  5198.5  5200.4  5232.9  5245.8  5290.7  5302.7  5325.3
  5340.3    5353  5359.7  5371.7  5379.2  5383.3  5389.4  5392.5  5407.1
  566.09  562.54  562.07  562.21  562.07  562.35   562.3  562.28  562.27  562.25
  562.23  562.21   562.2   562.2  562.24  562.24  562.27  562.28  562.25  562.15
   562.1   562.5  562.69  562.84  562.85  563.03   563.1  563.34  563.41  564.23
  564.48  564.69  564.79  564.99   565.3  565.33  565.54  565.64  563.61
  566.09  562.53  562.01  561.87  561.69  560.93  560.85  560.19  559.38  557.89
  558.18  557.85  558.25   560.2  560.24  557.05  557.61  557.24  557.34  557.01
  557.02  557.16  557.27  557.88  557.98  558.72  559.49  560.13  560.62  561.55
  561.64  562.13     562  562.43   562.7  562.85  563.07  563.28  563.61
  4601.2  4759.7  4768.2    4773    4780  4808.7  4811.8    4824  4860.6  4886.3
  4925.1  4944.6 4973.91    4974 5025.89    5026  5044.7  5062.9    5069  5085.4
  5091.1    5135  5169.7  5198.5  5200.4  5232.9  5245.8  5290.7  5302.7  5325.3
  5340.3    5353  5359.7  5371.7  5379.2  5383.3  5389.4  5392.5  5407.1
  566.09  562.54  562.07  562.21  562.07  562.35   562.3  562.28  562.27  562.25
  562.23  562.21   562.2   562.2  562.24  562.24  562.27  562.28  562.25  562.15
   562.1   562.5  562.69  562.84  562.85  563.03   563.1  563.34  563.41  564.23
  564.48  564.69  564.79  564.99   565.3  565.33  565.54  565.64  563.61
  565.84  562.28  561.76  561.62  561.44  560.68   560.6  559.94  559.13  557.64
  557.93   557.6     558  559.95  559.99   556.8  557.36  556.99  557.09  556.76
  556.77  556.91  557.02  557.63  557.73  558.47  559.24  559.88  560.37   561.3
  561.39  561.88  561.75  562.18  562.45   562.6  562.82  563.03  563.36
Pier Skew, UpSta & Num, DnSta & Num=,4981.4, 2 ,4981.4, 2 , 0 , 0 , 0 ,,
       1       1
  557.22   561.2
       1       1
  556.97  560.95
Pier Skew, UpSta & Num, DnSta & Num=,4993.8, 2 ,4993.8, 2 , 0 , 0 , 0 ,,
       1       1
   551.3   561.2
       1       1
  551.05  560.95
Pier Skew, UpSta & Num, DnSta & Num=,5006.2, 2 ,5006.2, 2 , 0 , 0 , 0 ,,
       1       1
   551.3  561.21
       1       1
  551.05  560.96
Pier Skew, UpSta & Num, DnSta & Num=,5018.5, 2 ,5018.5, 2 , 0 , 0 , 0 ,,
       1       1
  555.81  561.23
       1       1
  555.56  560.98
Abutment Skew #Up #Dn=, 2 , 2
 4973.80 4975.20
  560.20  558.26
 4973.80 4975.20
  559.95  558.01
Abutment Skew #Up #Dn=, 2 , 2
 5024.70 5026.09
  557.01  560.24
 5024.70 5026.09
  556.76  559.99
BR Coef= 1 , 1 , 0 ,1.25, 0 ,,,0.8,0,2,0,
Wspro=,,,, 1 ,,,, 0 ,,,, 0 ,,,,-1 ,-1 ,-1 , 0 , 0 , 0 , 0 , 0
BC Design=,, 0 ,, 0 ,,,,,,
BR U #Sta/Elev= 69
  4601.2  566.09  4623.4  565.59  4652.5  564.94    4722  563.38  4722.4  563.37
  4746.1  562.84  4749.9  562.75  4759.7  562.53  4768.2  562.01  4768.5  561.99
    4773  561.87    4780  561.69  4808.7  560.93  4811.8  560.85  4812.7   560.8
    4824  560.19  4860.6  559.38  4886.3  557.89  4925.1  558.18  4929.8   558.1
  4944.6  557.85  4957.2  558.02 4973.91  558.25    4974  558.25  4975.2  558.26
  4976.4  558.28  4983.4   558.2  4985.5   556.7    4989   552.3  4999.9   552.3
  5001.5   552.3    5011   552.3  5014.5   556.7  5024.7  557.01 5025.89  557.04
    5026  557.05  5044.7  557.61  5059.9   557.3  5062.9  557.24    5069  557.34
  5081.3  557.09  5085.4  557.01  5086.1  557.04  5086.9  557.01  5091.1  557.02
    5135  557.16  5169.7  557.27  5198.5  557.88  5200.4  557.98  5232.9  558.72
  5245.8  559.49  5290.7  560.13  5302.7  560.62  5304.9  560.71  5305.2  560.73
  5305.6  560.74  5324.5  561.52  5325.1  561.54  5325.3  561.55  5340.3  561.64
    5353  562.13  5359.7     562  5371.7  562.43  5379.2   562.7  5383.3  562.85
  5389.4  563.07  5392.1  563.27  5392.5  563.28  5407.1  563.61
BR U #Mann= 3
 4601.20    0.15  4985.5    0.05  5014.5    0.15
BR U Banks=4985.50,5014.50
BR D #Sta/Elev= 69
  4601.2  565.84  4623.4  565.34  4652.5  564.69    4722  563.13  4722.4  563.12
  4746.1  562.59  4749.9   562.5  4759.7  562.28  4768.2  561.76  4768.5  561.74
    4773  561.62    4780  561.44  4808.7  560.68  4811.8   560.6  4812.7  560.55
    4824  559.94  4860.6  559.13  4886.3  557.64  4925.1  557.93  4929.8  557.85
  4944.6   557.6  4957.2  557.77 4973.91     558    4974     558  4975.2  558.01
  4976.4  558.03  4983.4  557.95  4985.5  556.45    4989  552.05  4999.9  552.05
  5001.5  552.05    5011  552.05  5014.5  556.45  5024.7  556.76 5025.89  556.79
    5026   556.8  5044.7  557.36  5059.9  557.05  5062.9  556.99    5069  557.09
  5081.3  556.84  5085.4  556.76  5086.1  556.79  5086.9  556.76  5091.1  556.77
    5135  556.91  5169.7  557.02  5198.5  557.63  5200.4  557.73  5232.9  558.47
  5245.8  559.24  5290.7  559.88  5302.7  560.37  5304.9  560.46  5305.2  560.48
  5305.6  560.49  5324.5  561.27  5325.1  561.29  5325.3   561.3  5340.3  561.39
    5353  561.88  5359.7  561.75  5371.7  562.18  5379.2  562.45  5383.3   562.6
  5389.4  562.82  5392.1  563.02  5392.5  563.03  5407.1  563.36
BR D #Mann= 3
 4601.20    0.15  4985.5    0.05  5014.5    0.15
BR D Banks=4985.50,5014.50

Type RM Length L Ch R = 1 ,32354.3,416.75,416.75,416.75
XS GIS Cut Line= 3
      1877467.46       807766.45      1877324.65       807393.73
      1877187.78       807010.70
BEGIN DESCRIPTION:
Downstream Section of Bridge/Culvert/Weir
END DESCRIPTION:
#Sta/Elev= 30
  4601.2  565.81  4759.7  562.25  4768.5  561.71  4811.8  560.57    4824  559.91
  4860.6   559.1  4886.3  557.61  4925.1   557.9  4944.6  557.57  4976.4     558
  4983.4  557.92  4985.5  556.42    4989  552.02    5011  552.02  5014.5  556.42
  5044.7  557.33  5062.9  556.96    5069  557.06  5085.4  556.73  5169.7  556.99
  5232.9  558.44  5245.8  559.21  5290.7  559.85  5325.3  561.27  5340.3  561.36
    5353  561.85  5359.7  561.72  5389.4  562.79  5392.1  562.99  5407.1  563.33
#Mann= 3 , 1 , 0
 4601.20    0.15       0  4985.5    0.05       0  5014.5    0.15       0
#XS Ineff= 2 , 0
       0    4963   562.2    5036       0   562.2
Bank Sta=4985.50,5014.50
Exp/Cntr=0.5,0.3

Type RM Length L Ch R = 1 ,31937.5,514.9,514.9,514.9
XS GIS Cut Line= 3
      1877438.47       807878.36      1877679.04       807585.28
      1877768.73       807496.89
BEGIN DESCRIPTION:
Varnals Creek 3.0
END DESCRIPTION:
#Sta/Elev= 24
  4622.2  567.65  4632.6  567.47  4688.7  564.45  4779.2  563.33  4794.6  562.72
  4836.2     560  4845.6  559.14  4897.5  557.47  4912.1   557.5  4934.9  556.88
  4975.5  556.88    4985  553.69  4989.5  550.69  5010.5  550.69    5015  553.69
  5064.5  556.89  5064.6  556.88  5071.8  559.44  5085.8  562.29  5088.8  562.77
  5109.1  565.28  5125.2  567.97  5126.2  568.25  5127.3  568.38
#Mann= 3 , 1 , 0
 4622.20    0.14       0    4985   0.045       0    5015    0.14       0
Bank Sta=4985.00,5015.00
Exp/Cntr=0.3,0.1

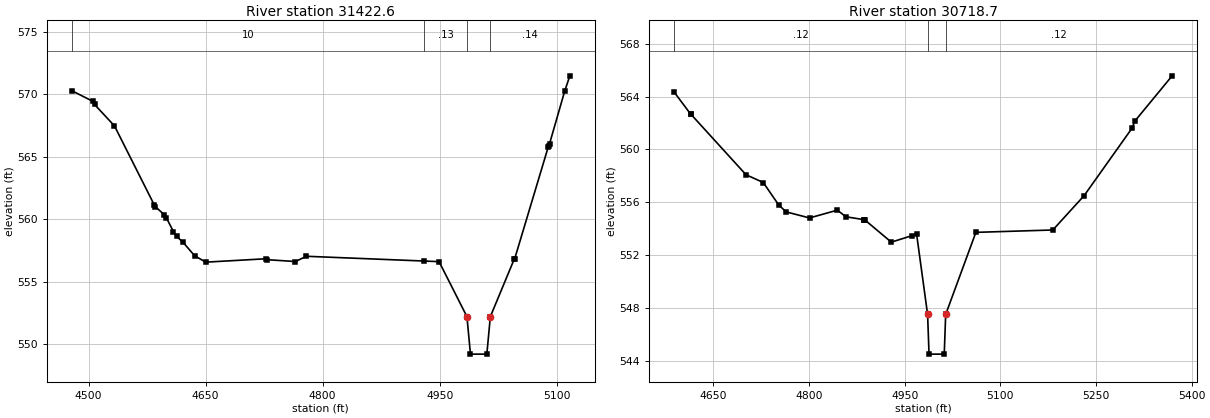
Type RM Length L Ch R = 1 ,31422.6,703.9,703.9,703.9
XS GIS Cut Line= 3
      1877746.85       808285.12      1878088.56       807885.83
      1878156.65       807795.58
BEGIN DESCRIPTION:
Varnals Creek 2.0
END DESCRIPTION:
#Sta/Elev= 30
  4478.3  570.28  4505.5  569.42  4507.7  569.17  4533.3  567.45  4584.5   561.1
  4585.6     561  4597.2  560.33  4599.9  560.08  4608.9  558.99  4612.9  558.61
    4621  558.15    4636  557.06  4650.3  556.55  4727.1  556.82  4728.3  556.75
  4765.2   556.6  4779.2  557.02  4929.9  556.64  4949.3  556.59    4985  552.19
  4989.5  549.19  5010.5  549.19    5015  552.19  5045.8  556.82    5046  556.78
    5089  565.73  5090.1  565.88  5090.9  566.03  5110.2  570.22  5116.9  571.46
#Mann= 4 , 1 , 0
 4478.30      10       0  4929.9    0.13       0    4985   0.045       0
    5015    0.14       0
Bank Sta=4985.00,5015.00
Exp/Cntr=0.3,0.1

Type RM Length L Ch R = 1 ,30718.7,0,0,0
XS GIS Cut Line= 4
      1878221.84       808791.10      1878382.82       808454.17
      1878392.19       808354.48      1878548.07       808089.00
BEGIN DESCRIPTION:
Varnals Creek 1.0
END DESCRIPTION:
#Sta/Elev= 26
    4588  564.37  4614.5  562.66    4615  562.65  4701.1  558.09  4728.2   557.5
  4752.3  555.81    4764  555.28  4800.7  554.82  4844.4  555.41  4857.7  554.91
  4886.2  554.69  4886.8  554.67  4887.5  554.67    4929  552.99  4961.4  553.48
  4968.7  553.59  4985.9  547.52 4988.15  544.52    5012  544.52 5014.25  547.52
  5061.6  553.73  5182.3  553.91  5231.4  556.51  5306.2  561.59  5311.3  562.17
  5369.4  565.57
#Mann= 3 , 1 , 0
 4588.00    0.12       0  4985.9   0.042       0 5014.25    0.12       0
Bank Sta=4985.90,5014.25
Exp/Cntr=0.3,0.1

Chan Stop Cuts=-1